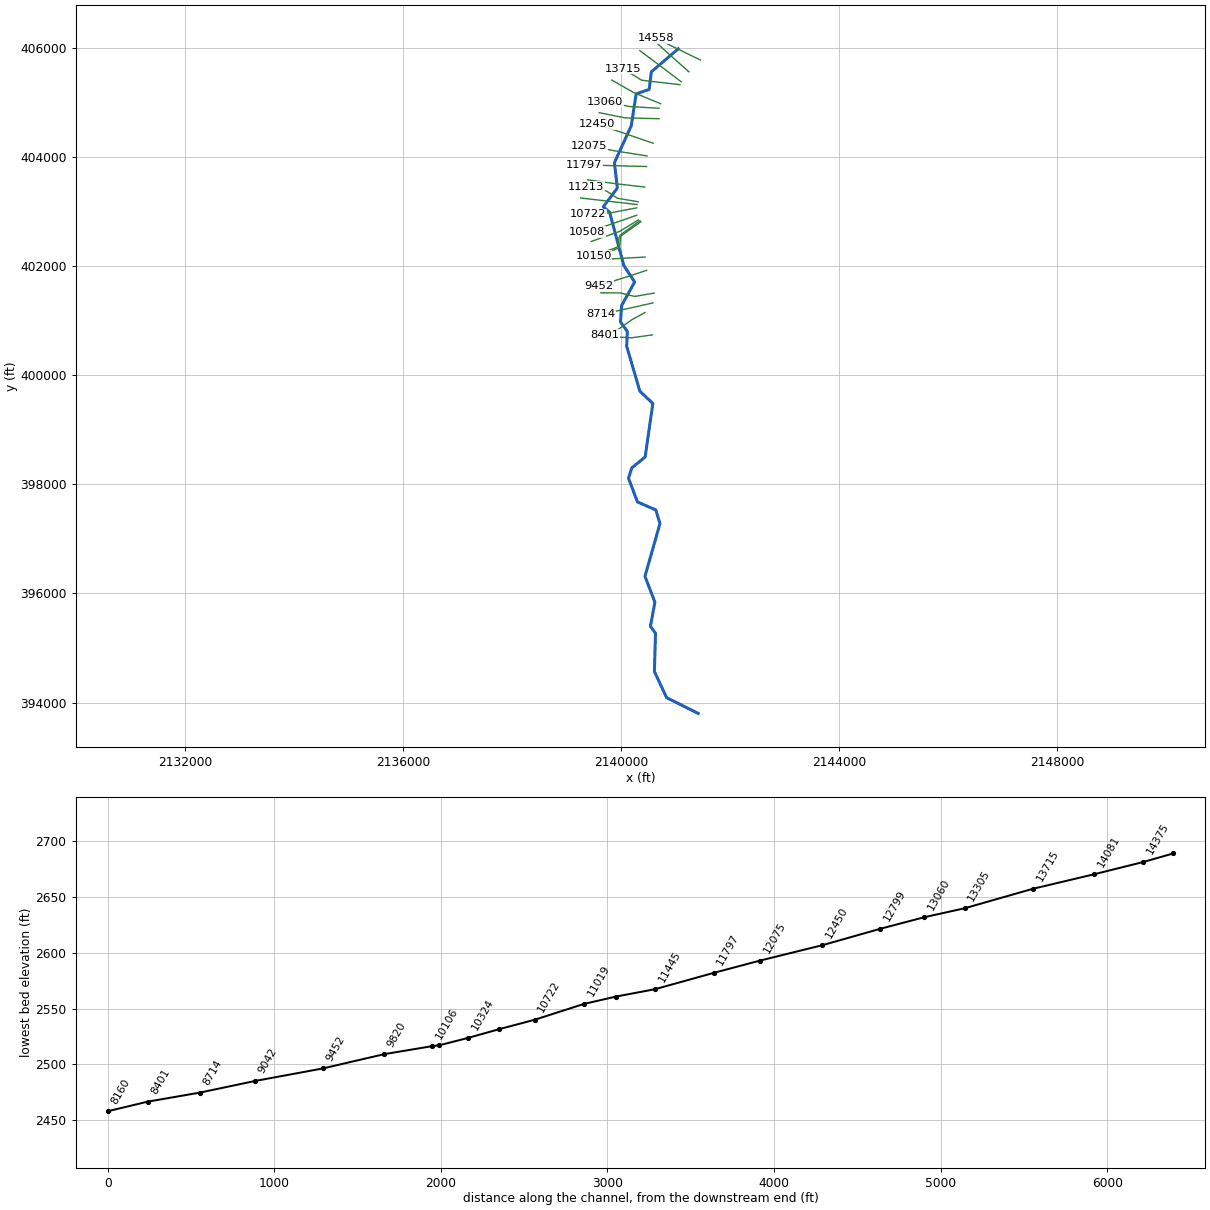
--- PNTHRCMPCK.prj (project) ---

Proj Title=PNTHRCMPCK
Current Plan=p01
Default Exp/Contr=0.3,0.1
English Units
Geom File=g01
Flow File=f01
Plan File=p01
Y Axis Title=Elevation
X Axis Title(PF)=Main Channel Distance
X Axis Title(XS)=Station
BEGIN DESCRIPTION:
Stream Name- Panther Camp Creek
Flood Zone: Zone A
Greenbrier County, WV
County-Wide Study
WVDHSEM-2018-3, Flood Risk Project
HEC-RAS Version: 5.0.7
General Notes:
For the Hydrology Regression was used.
END DESCRIPTION:
DSS Export Rating Curves= 0
DSS Export Rating Curve Sorted= 0
DSS Export Volume Flow Curves= 0
DXF Filename=A3a.
DXF OffsetX= 0
DXF OffsetY= 0
DXF ScaleX= 1
DXF ScaleY= 10

--- PNTHRCMPCK.p01 (plan) ---

Plan Title=Floodplain
Program Version=5.07
Short Identifier=Floodplain
Geom File=g01
Flow File=f01
Subcritical Flow
K Sum by GR= 0
Std Step Tol= 0.01
Critical Tol= 0.01
Num of Std Step Trials= 20
Max Error Tol= 0.3
Flow Tol Ratio= 0.001
Split Flow NTrial= 30
Split Flow Tol= 0.02
Split Flow Ratio= 0.02
Log Output Level= 0
Friction Slope Method= 1
Unsteady Friction Slope Method= 2
Unsteady Bridges Friction Slope Method= 1
Parabolic Critical Depth
Global Vel Dist= 0 , 0 , 0
Global Log Level= 0
CheckData=True
Encroach Param=-1 ,0,0, 0
Computation Interval=1MIN
Output Interval=1HOUR
Instantaneous Interval=1HOUR
Mapping Interval=1HOUR
Computation Time Step Use Courant=        0
Computation Time Step Use Time Series=    0
Computation Time Step Count To Double=0
Computation Time Step Max Doubling=0
Computation Time Step Max Halving=0
Computation Time Step Residence Courant=0
Run HTab= 0
Run UNet= 0
Run Sediment= 0
Run PostProcess= 0
Run WQNet= 0
Run RASMapper= 0
UNET Theta= 1
UNET Theta Warmup= 1
UNET ZTol= 0.02
UNET ZSATol= 0.02
UNET MxIter= 20
UNET Max Iter WO Improvement= 0
UNET MaxInSteps= 0
UNET DtIC= 0
UNET DtMin= 0
UNET MaxCRTS= 20
UNET WFStab= 2
UNET SFStab= 1
UNET WFX= 1
UNET SFX= 1
UNET 1D Methodology=Finite Difference
UNET DSS MLevel= 4
UNET Pardiso=0
UNET DZMax Abort= 100
UNET Use Existing IB Tables=-1
UNET Froude Reduction=False
UNET Froude Limit= 0.8
UNET Froude Power= 4
UNET D1 Cores= 0
UNET D2 Coriolis=0
UNET D2 Cores= 0
UNET D2 Theta= 1
UNET D2 Theta Warmup= 1
UNET D2 Z Tol= 0.01
UNET D2 Volume Tol= 0.01
UNET D2 Max Iterations= 20
UNET D2 Equation= 0
UNET D2 RampUpFraction=0.1
UNET D2 TimeSlices= 1
UNET D2 BCVolumeCheck=0
UNET D1D2 MaxIter= 0
UNET D1D2 ZTol=0.01
UNET D1D2 QTol=0.1
UNET D1D2 MinQTol=1
Write IC File= 0
Write IC File at Fixed DateTime=0
Write IC File at Sim End=0
Echo Input=False
Echo Parameters=False
Echo Output=False
Write Detailed= 0
HDF Write Warmup=0
HDF Write Time Slices=0
HDF Flush=0
HDF Face Node Velocities=0
HDF Compression= 1
HDF Chunk Size= 1
HDF Spatial Parts= 1
HDF Use Max Rows=0
HDF Fixed Rows= 1
Calibration Method= 0
Calibration Iterations= 20
Calibration Max Change=0.05
Calibration Tolerance=0.2
Calibration Maximum=1.5
Calibration Minimum=0.5
Calibration Optimization Method= 1
WQ AD Non Conservative
WQ ULTIMATE=-1
WQ Max Comp Step=1HOUR
WQ Output Interval=15MIN
WQ Output Selected Increments= 0
WQ Output face flow=0
WQ Output face velocity=0
WQ Output face area=0
WQ Output face dispersion=0
WQ Output cell volume=0
WQ Output cell surface area=0
WQ Output cell continuity=0
WQ Output cumulative cell continuity=0
WQ Output face conc=0
WQ Output face dconc_dx=0
WQ Output face courant=0
WQ Output face peclet=0
WQ Output face adv mass=0
WQ Output face disp mass=0
WQ Output cell mass=0
WQ Output cell source sink temp=0
WQ Output nsm pathways=0
WQ Output nsm derived pathways=0
WQ Output MaxMinRange=-1
WQ Daily Max Min Mean=-1
WQ Daily Range=0
WQ Daily Time=0
WQ Create Restart=0
WQ Fixed Restart=0
WQ System Summary=0
WQ Write To DSS=0
WQ Use Fixed Temperature=0
Sorting and Armoring Iterations= 10
XS Update Threshold= 0.02
Bed Roughness Predictor= 0
Hydraulics Update Threshold= 0.02
Energy Slope Method= 1
Volume Change Method= 1
Sediment Retention Method= 0
XS Weighting Method= 0
Number of US Weighted Cross Sections= 1
Number of DS Weighted Cross Sections= 1
Upstream XS Weight=0
Main XS Weight=1
Downstream XS Weight=0
Number of DS XS's Weighted with US Boundary= 1
Upstream Boundary Weight= 1
Weight of XSs Associated with US Boundary= 0
Number of US XS's Weighted with DS Boundary= 1
Downstream Boundary Weight= 0.5
Weight of XSs Associated with DS Boundary= 0.5
Percentile Method= 0
Sediment Output Level= 3
Mass or Volume Output= 0
Output Increment Type= 1
Profile and TS Output Increment= 1
XS Output Flag= 0
XS Output Increment= 10
Write Gradation File= 0
Read Gradation Hotstart= 0
Write HDF5 File= 1
Write Binary Output= 1
Write DSS Sediment File= 0
SV Curve= 0
Specific Gage Flag= 0

--- PNTHRCMPCK.f01 (steady flow) ---

Flow Title=Flow
Program Version=5.07
Number of Profiles= 6
Profile Names=f1p,f10p,f4p,f2p,f02p,f1pplus
River Rch & RM=BEVERLYFK,Main            ,776
     323     167     225     272     456     478
River Rch & RM=BEVERLYFK,Main            ,220
     537     283     377     454     751     794
River Rch & RM=BOGGSRN,Main            ,1733
     558     295     392     472     780     825
River Rch & RM=DRYRN,Main            ,9301
     532     280     373     450     744     787
River Rch & RM=DRYRN,Main            ,8316
     594     314     418     503     829     878
River Rch & RM=DRYRN,Main            ,6862
     769     411     544     653    1070    1140
River Rch & RM=DRYRN,Main            ,5213
     898     483     637     763    1240    1330
River Rch & RM=DRYRN,Main            ,259
    1110     604     793     948    1540    1650
River Rch & RM=PNTHRCMPCK,Main            ,14558
     513     270     359     434     718     758
River Rch & RM=PNTHRCMPCK,Main            ,13060
     599     317     422     508     836     886
River Rch & RM=PNTHRCMPCK,Main            ,10150
     873     469     619     742    1210    1290
River Rch & RM=PNTHRCMPCK,Main            ,8160
     976     526     693     830    1350    1440
River Rch & RM=PNTHRCMPCK,Main            ,6420
    1080     588     772     923    1500    1600
River Rch & RM=RCKCMPRN,Main            ,4355
     581     307     409     492     812     860
River Rch & RM=RCKCMPRN,Main            ,1618
     692     368     488     586     963    1020
River Rch & RM=ROBBINSRN,Main            ,27789
     907     488     643     771    1260    1340
River Rch & RM=ROBBINSRN,Main            ,27014
    1170     638     837    1000    1620    1740
River Rch & RM=ROBBINSRN,Main            ,21785
    1330     728     953    1140    1830    1970
River Rch & RM=ROBBINSRN,Main            ,16781
    1830    1010    1320    1570    2500    2710
River Rch & RM=ROBBINSRN,Main            ,10962
    2050    1140    1480    1750    2790    3030
River Rch & RM=SPRINGCKT3,Main            ,6529
     583     309     410     494     815     863
River Rch & RM=SPRINGCKT3,Main            ,3093
     683     363     482     579     951    1010
River Rch & RM=SPRINGCKT3,Main            ,434
     860     462     609     730    1190    1270
Boundary for River Rch & Prof#=BEVERLYFK,Main            , 1
Up Type= 0
Dn Type= 3
Dn Slope=0.045649
Boundary for River Rch & Prof#=BEVERLYFK,Main            , 2
Up Type= 0
Dn Type= 3
Dn Slope=0.045649
Boundary for River Rch & Prof#=BEVERLYFK,Main            , 3
Up Type= 0
Dn Type= 3
Dn Slope=0.045649
Boundary for River Rch & Prof#=BEVERLYFK,Main            , 4
Up Type= 0
Dn Type= 3
Dn Slope=0.045649
Boundary for River Rch & Prof#=BEVERLYFK,Main            , 5
Up Type= 0
Dn Type= 3
Dn Slope=0.045649
Boundary for River Rch & Prof#=BEVERLYFK,Main            , 6
Up Type= 0
Dn Type= 3
Dn Slope=0.045649
Boundary for River Rch & Prof#=BOGGSRN,Main            , 1
Up Type= 0
Dn Type= 3
Dn Slope=0.043074
Boundary for River Rch & Prof#=BOGGSRN,Main            , 2
Up Type= 0
Dn Type= 3
Dn Slope=0.043074
Boundary for River Rch & Prof#=BOGGSRN,Main            , 3
Up Type= 0
Dn Type= 3
Dn Slope=0.043074
Boundary for River Rch & Prof#=BOGGSRN,Main            , 4
Up Type= 0
Dn Type= 3
Dn Slope=0.043074
Boundary for River Rch & Prof#=BOGGSRN,Main            , 5
Up Type= 0
Dn Type= 3
Dn Slope=0.043074
Boundary for River Rch & Prof#=BOGGSRN,Main            , 6
Up Type= 0
Dn Type= 3
Dn Slope=0.043074
Boundary for River Rch & Prof#=DRYRN,Main            , 1
Up Type= 0
Dn Type= 3
Dn Slope=0.021282
Boundary for River Rch & Prof#=DRYRN,Main            , 2
Up Type= 0
Dn Type= 3
Dn Slope=0.021282
Boundary for River Rch & Prof#=DRYRN,Main            , 3
Up Type= 0
Dn Type= 3
Dn Slope=0.021282
Boundary for River Rch & Prof#=DRYRN,Main            , 4
Up Type= 0
Dn Type= 3
Dn Slope=0.021282
Boundary for River Rch & Prof#=DRYRN,Main            , 5
Up Type= 0
Dn Type= 3
Dn Slope=0.021282
Boundary for River Rch & Prof#=DRYRN,Main            , 6
Up Type= 0
Dn Type= 3
Dn Slope=0.021282
Boundary for River Rch & Prof#=PNTHRCMPCK,Main            , 1
Up Type= 0
Dn Type= 3
Dn Slope=0.02712
Boundary for River Rch & Prof#=PNTHRCMPCK,Main            , 2
Up Type= 0
Dn Type= 3
Dn Slope=0.02712
Boundary for River Rch & Prof#=PNTHRCMPCK,Main            , 3
Up Type= 0
Dn Type= 3
Dn Slope=0.02712
Boundary for River Rch & Prof#=PNTHRCMPCK,Main            , 4
Up Type= 0
Dn Type= 3
Dn Slope=0.02712
Boundary for River Rch & Prof#=PNTHRCMPCK,Main            , 5
Up Type= 0
Dn Type= 3
Dn Slope=0.02712
Boundary for River Rch & Prof#=PNTHRCMPCK,Main            , 6
Up Type= 0
Dn Type= 3
Dn Slope=0.02712
Boundary for River Rch & Prof#=RCKCMPRN,Main            , 1
Up Type= 0
Dn Type= 3
Dn Slope=0.013802
Boundary for River Rch & Prof#=RCKCMPRN,Main            , 2
Up Type= 0
Dn Type= 3
Dn Slope=0.013802
Boundary for River Rch & Prof#=RCKCMPRN,Main            , 3
Up Type= 0
Dn Type= 3
Dn Slope=0.013802
Boundary for River Rch & Prof#=RCKCMPRN,Main            , 4
Up Type= 0
Dn Type= 3
Dn Slope=0.013802
Boundary for River Rch & Prof#=RCKCMPRN,Main            , 5
Up Type= 0
Dn Type= 3
Dn Slope=0.013802
Boundary for River Rch & Prof#=RCKCMPRN,Main            , 6
Up Type= 0
Dn Type= 3
Dn Slope=0.013802
Boundary for River Rch & Prof#=ROBBINSRN,Main            , 1
Up Type= 0
Dn Type= 3
Dn Slope=0.010317
Boundary for River Rch & Prof#=ROBBINSRN,Main            , 2
Up Type= 0
Dn Type= 3
Dn Slope=0.010317
Boundary for River Rch & Prof#=ROBBINSRN,Main            , 3
Up Type= 0
Dn Type= 3
Dn Slope=0.010317
Boundary for River Rch & Prof#=ROBBINSRN,Main            , 4
Up Type= 0
Dn Type= 3
Dn Slope=0.010317
Boundary for River Rch & Prof#=ROBBINSRN,Main            , 5
Up Type= 0
Dn Type= 3
Dn Slope=0.010317
Boundary for River Rch & Prof#=ROBBINSRN,Main            , 6
Up Type= 0
Dn Type= 3
Dn Slope=0.010317
Boundary for River Rch & Prof#=SPRINGCKT3,Main            , 1
Up Type= 0
Dn Type= 3
Dn Slope=0.016207
Boundary for River Rch & Prof#=SPRINGCKT3,Main            , 2
Up Type= 0
Dn Type= 3
Dn Slope=0.016207
Boundary for River Rch & Prof#=SPRINGCKT3,Main            , 3
Up Type= 0
Dn Type= 3
Dn Slope=0.016207
Boundary for River Rch & Prof#=SPRINGCKT3,Main            , 4
Up Type= 0
Dn Type= 3
Dn Slope=0.016207
Boundary for River Rch & Prof#=SPRINGCKT3,Main            , 5
Up Type= 0
Dn Type= 3
Dn Slope=0.016207
Boundary for River Rch & Prof#=SPRINGCKT3,Main            , 6
Up Type= 0
Dn Type= 3
Dn Slope=0.016207
DSS Import GetInterval= 0
DSS Import GetPeak= 0
DSS Import FillOption= 0

--- PNTHRCMPCK.g01 (geometry) ---

Geom Title=Geometry
Program Version=5.07

River Reach=PNTHRCMPCK      ,Main
Reach XY= 30
2141046.81985147405985.1300213042140554.26014106405563.010130644
2140514.37997147405241.0301315642140276.11010681405158.920059562
2140185.92984097404573.7099438912139877.25985464403896.759854227
2139931.68002139403433.1098628942139673.77010414403087.450121149
2139789.17997831402989.6599624012140050.93011098402010.960148141
2140247.91987447401709.9801070542140009.25991872401276.770015478
2139989.29014239400977.430062979 2140114.7600358400801.740125641
2140102.40015239400531.7400094722140344.31994414399707.510030642
2140582.16986214 399483.350045892140440.61010589398500.870055482
2140195.37995331398301.2398773132140135.65992838398113.049964979
 2140300.2399798397676.9399448042140636.34987189 397531.10001339
2140712.60004747397280.8200021392140437.74003288396313.739915311
2140619.67995772395840.1299701482140538.43012021395397.769962475
2140630.80001423395269.3000750542140610.65996264394567.209943816
2140834.96003897394089.4300594782141412.29156147393800.840085477

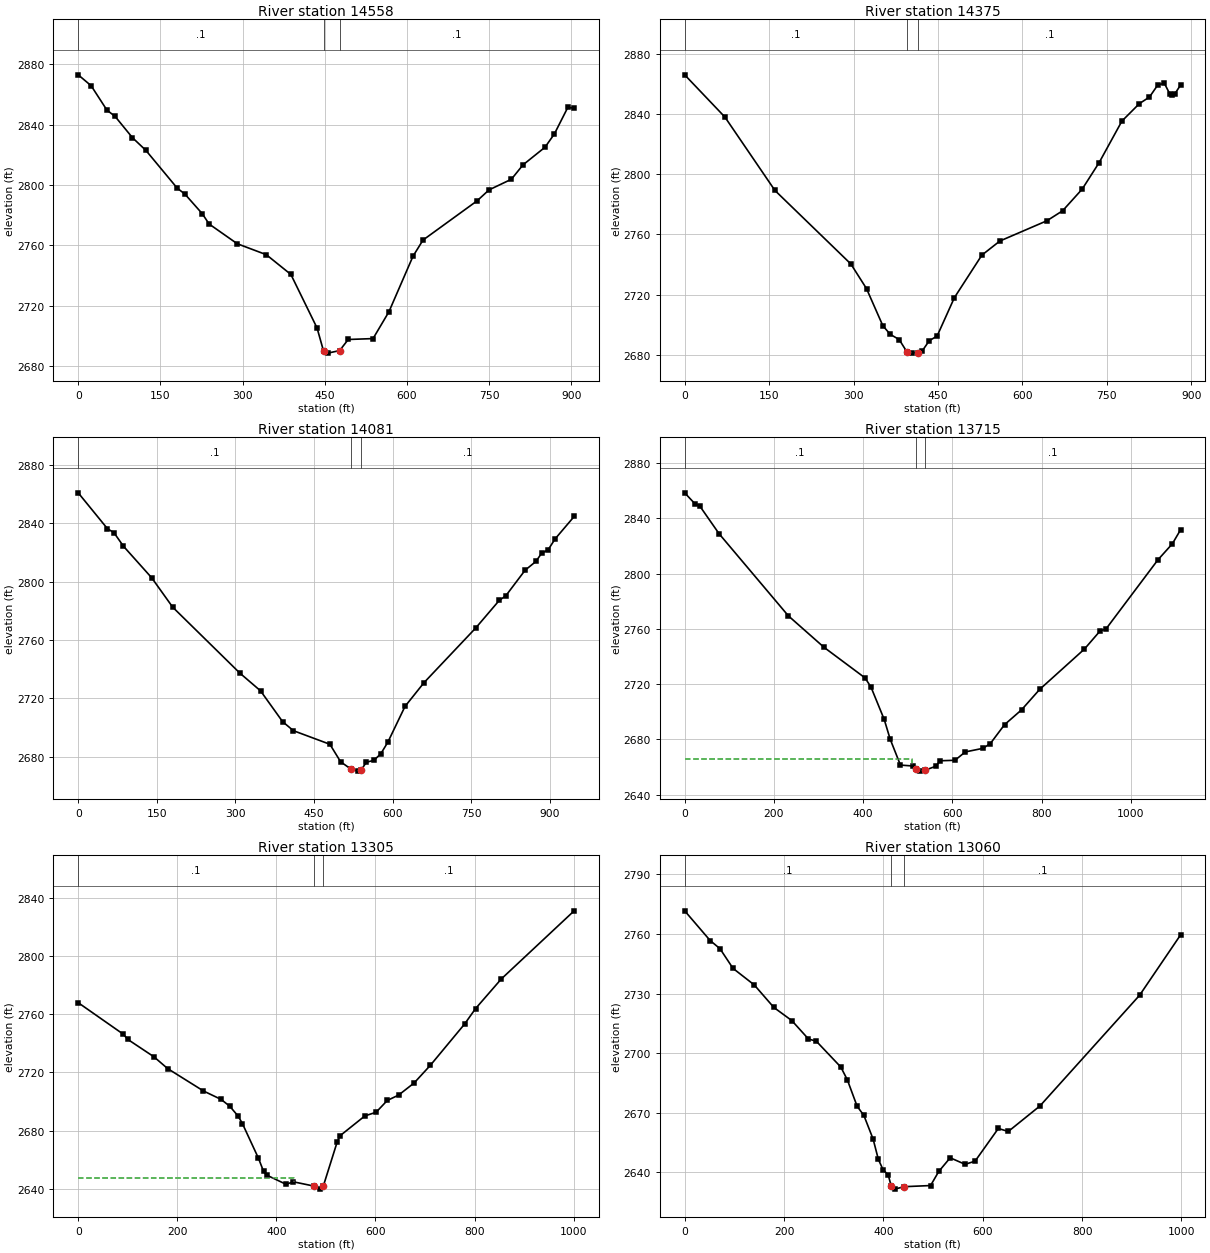
Type RM Length L Ch R = 1 ,14558   ,184.8,182.9,178
XS GIS Cut Line= 2
2141453.52343439405780.3961788122140639.72158431406177.531867474
#Sta/Elev= 30
       0 2872.91    23.6  2865.7    52.4 2849.57    67.4 2845.36      99 2831.32
   123.6 2822.89   180.6 2797.99   195.2 2793.82   226.6 2780.95     239 2774.18
   290.4 2761.11   343.4 2753.88   388.3 2740.79   436.1 2705.35  447.862690.194
   455.6 2688.72  477.282690.392     493 2697.75   538.3 2698.34   567.3 2716.09
   611.3 2752.88   629.6 2763.57   728.2 2789.49   750.1 2796.76   790.9  2803.8
   812.1 2813.31   852.3 2824.99   869.4 2833.78   893.9 2851.33   905.5 2850.87
#Mann= 3 ,-1 , 0
       0      .1       0  447.86    .045       0  477.28      .1       0
Bank Sta=447.86,477.28
XS Rating Curve= 0 ,0
Exp/Cntr=0.3,0.1

Type RM Length L Ch R = 1 ,14375   ,293.1,294.1,294.6
XS GIS Cut Line= 3
2141243.02024648405564.4674768152140878.43665805405887.818208054
2140587.63802706406153.660196066
#Sta/Elev= 30
       0 2866.36    71.5 2838.22   160.4 2789.33   295.3 2740.36   323.1 2723.95
   352.1 2699.26   365.3 2693.47   381.2 2690.02  394.732681.875   404.4 2680.97
  415.452681.224   422.3 2682.53   434.6 2689.23   448.6 2692.36   479.3 2717.94
   528.1 2746.25   560.1 2755.65   643.7 2769.15   671.6  2775.8   706.4 2790.24
   736.6 2807.95     777 2835.56   808.1 2847.21   825.9 2851.54   841.1 2859.81
   852.6 2860.59     862 2853.69   865.9 2853.15   871.3 2853.87   881.3 2859.58
#Mann= 3 ,-1 , 0
       0      .1       0  394.73    .045       0  415.45      .1       0
Bank Sta=394.73,415.45
XS Rating Curve= 0 ,0
Exp/Cntr=0.3,0.1

Type RM Length L Ch R = 1 ,14081   ,360,365.9,370.6
XS GIS Cut Line= 3
2141099.42670164405381.8694168032140776.44014288 405628.48670572
2140343.49743922405951.837436974
#Sta/Elev= 30
       0  2860.9    55.9 2836.27    68.2 2833.57    86.4 2824.27   140.2 2802.66
   180.4 2782.46   308.7 2737.21     348 2725.11   390.2 2703.95   410.8 2697.76
   480.4 2688.45   500.9 2676.45  519.91 2671.61   533.6 2670.03  540.24 2670.85
     550 2676.16   564.1 2677.37   577.5 2681.86     591 2689.85   623.8 2714.39
   660.2 2730.76   758.9 2768.24   803.9 2787.19   816.2 2790.27   853.1 2807.84
   873.6 2813.81   884.5  2819.4     897 2821.83   910.4 2829.32   946.7 2844.67
#Mann= 3 ,-1 , 0
       0      .1       0  519.91    .045       0  540.24      .1       0
Bank Sta=519.91,540.24
XS Rating Curve= 0 ,0
Exp/Cntr=0.3,0.1

Type RM Length L Ch R = 1 ,13715   ,411.7,409.6,405.5
XS GIS Cut Line= 3
2141079.17477363405327.922346234 2140379.3047823405409.302432805
2140032.08270772405620.891248479
#Sta/Elev= 30
       0 2858.47    23.2 2850.46    34.2 2848.75    77.2 2828.82   232.4 2769.43
   312.2 2746.69   404.1 2724.57   417.4 2717.94   447.1 2694.47   460.3 2680.36
   483.4 2661.49   512.4 2660.79  517.762658.675   527.2 2657.11  537.792657.679
   562.7 2660.65   572.6 2664.61   605.6 2664.96   628.7    2671   668.4 2673.61
   684.9 2677.07   716.6  2690.7   754.7 2701.43   795.4 2716.24   895.7 2745.44
   931.6 2758.85   943.4 2759.72  1060.4 2810.02  1092.8 2821.65  1111.2 2831.81
#Mann= 3 ,-1 , 0
       0      .1       0  517.76    .045       0  537.79      .1       0
#XS Ineff= 2 , 0
          509.82 2666.19
Permanent Ineff=
       F       F
Bank Sta=517.76,537.79
XS Rating Curve= 0 ,0
Exp/Cntr=0.3,0.1

Type RM Length L Ch R = 1 ,13305   ,241.3,245,247.3
XS GIS Cut Line= 3
2140727.61215656404977.4450288122140234.99043839405181.438059136
2139828.08967739405412.557675645
#Sta/Elev= 30
       0 2767.84    91.3 2746.11    99.8 2742.67   152.8 2730.67   180.4 2722.59
   252.8 2707.17   288.5 2701.36     306 2696.65   322.8 2689.89   331.4  2684.8
   363.7 2661.04   374.2 2651.89   380.7  2649.3   419.7    2643     434 2644.76
  475.812641.804   487.2 2639.71  494.982642.051   522.7 2672.06   528.6 2676.41
   578.7 2690.04   601.3 2692.54   623.9 2700.66   646.6 2704.31   678.1 2712.68
   710.7 2724.76   779.9 2753.15     802 2763.76   854.1 2784.17  1001.1 2830.98
#Mann= 3 ,-1 , 0
       0      .1       0  475.81    .045       0  494.98      .1       0
#XS Ineff= 2 , 0
          435.15  2647.7
Permanent Ineff=
       F       F
Bank Sta=475.81,494.98
XS Rating Curve= 0 ,0
Exp/Cntr=0.3,0.1

Type RM Length L Ch R = 1 ,13060   ,259.5,261.3,255.6
XS GIS Cut Line= 3
2140696.14502789404894.9796425552140156.86559464404927.531742811
2139707.64667681405017.592586309
#Sta/Elev= 30
       0  2771.7    51.3 2756.74      71 2752.66    97.4 2742.71   140.1 2734.39
   179.5 2723.06   215.7 2716.44   249.2 2707.17     265 2706.06   314.3 2693.06
   327.4 2686.66   347.1 2673.34   360.8 2668.66   379.4 2656.75   389.9 2646.56
   399.7  2641.2   409.6 2638.87  415.842633.112   422.7 2631.59  442.032632.821
     495 2633.39   511.5 2640.48   534.5 2647.37   564.5 2644.08   584.6 2645.67
   631.4 2662.12   651.5 2660.62   715.1 2673.44   915.8 2729.19   998.4 2759.61
#Mann= 3 ,-1 , 0
       0      .1       0  415.84    .045       0  442.03      .1       0
Bank Sta=415.84,442.03
XS Rating Curve= 0 ,0
Exp/Cntr=0.3,0.1

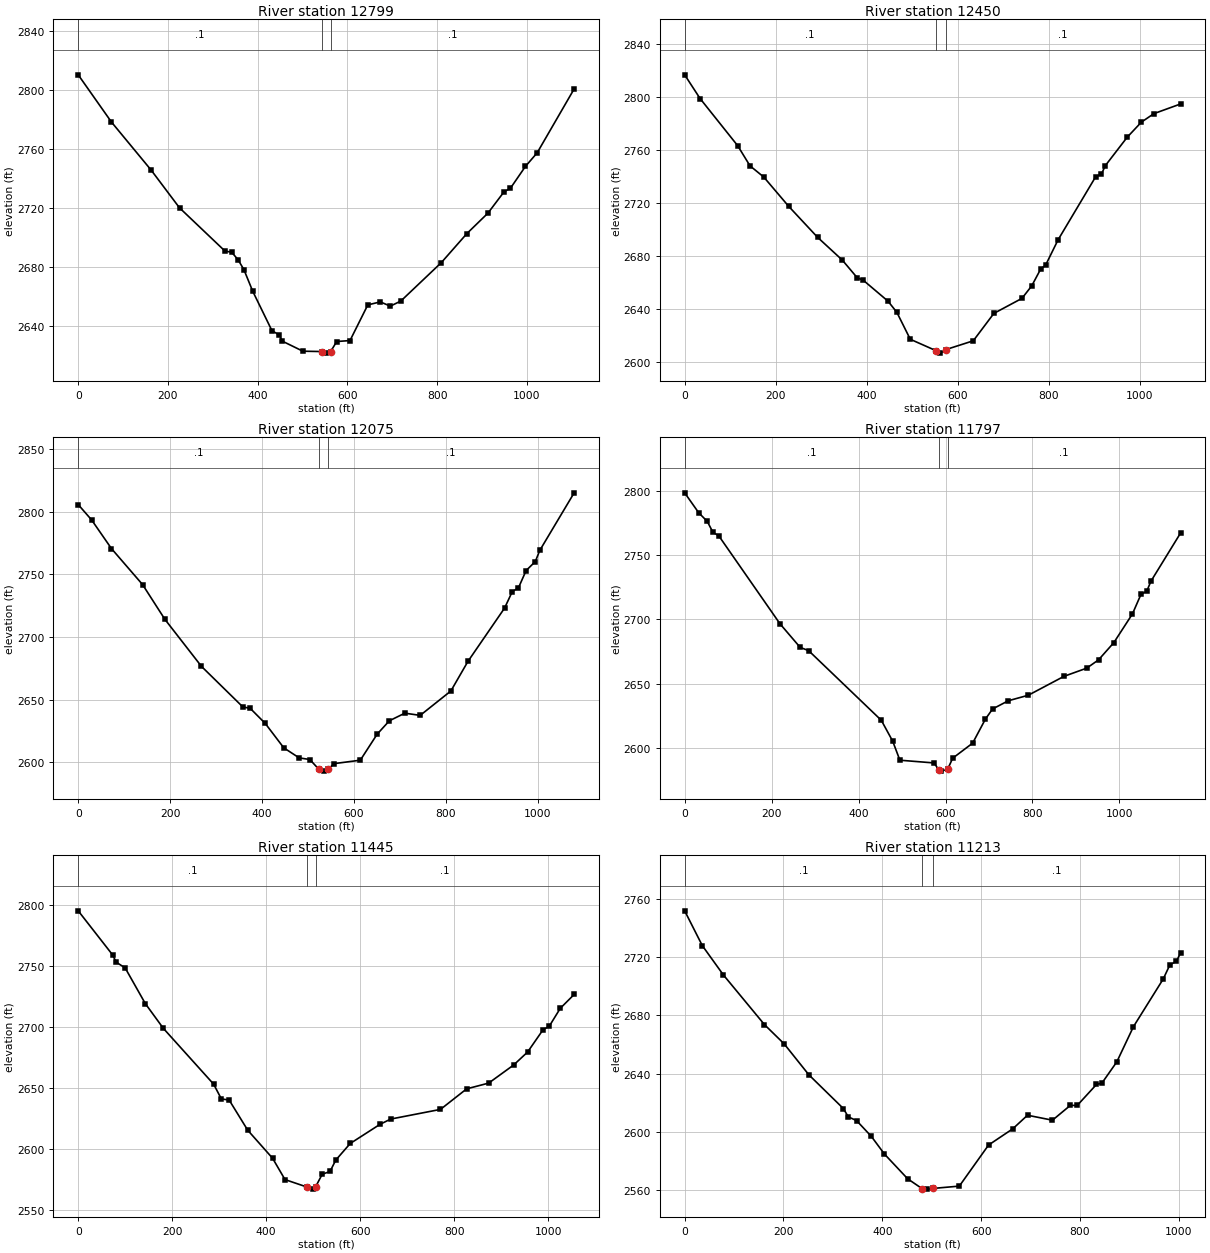
Type RM Length L Ch R = 1 ,12799   ,350.5,348.4,344.5
XS GIS Cut Line= 3
2140696.14502789 404704.00725548 2140067.8900508404720.283469647
2139600.22497563404814.684527561
#Sta/Elev= 30
       0 2810.49    74.2 2778.36   162.8 2745.66   225.8 2720.11   326.9 2690.79
   342.4 2689.87   356.5 2684.75   369.4  2678.1     389 2663.44   431.9 2636.62
   448.4 2633.68   454.9 2629.52   500.9 2622.67   542.82622.434   553.4 2621.36
   562.8 2622.46   576.3 2629.26   605.9 2629.89   645.6 2654.14   673.4 2656.18
   695.8 2653.29   719.2 2656.76   809.6 2682.91   866.5 2702.62   913.4  2716.5
   949.1 2730.92   963.6 2733.43     997 2748.25  1023.1 2757.47  1105.6 2800.92
#Mann= 3 ,-1 , 0
       0      .1       0   542.8    .045       0   562.8      .1       0
Bank Sta=542.8,562.8
XS Rating Curve= 0 ,0
Exp/Cntr=0.3,0.1

Type RM Length L Ch R = 1 ,12450   ,371.6,375,375.7
XS GIS Cut Line= 3
2140588.72332673 404253.703694152140011.46627913404452.271210387
2139555.73720372 404602.01074031
#Sta/Elev= 30
       0 2816.59    33.8 2798.73   116.5 2763.14   143.6 2747.93   173.9 2739.47
   228.5 2717.44     292 2694.07   346.5 2676.84   379.8  2663.3   391.6 2661.92
   446.9 2645.87   466.4 2637.43   495.9 2617.11  551.692608.624   561.6 2606.65
  574.052609.309   634.4 2615.95   679.7 2636.63   741.4 2647.95   762.9 2657.39
   782.9 2670.27   793.2 2672.86   820.8 2692.11   903.7 2739.85   916.2 2741.68
   924.4 2747.95   972.8 2769.53  1003.9 2780.89  1031.5 2787.32  1090.2 2794.62
#Mann= 3 ,-1 , 0
       0      .1       0  551.69    .045       0  574.05      .1       0
Bank Sta=551.69,574.05
XS Rating Curve= 0 ,0
Exp/Cntr=0.3,0.1

Type RM Length L Ch R = 1 ,12075   ,276.4,278,279
XS GIS Cut Line= 3
2140476.96108305404021.4987779712139915.98024964404109.389350221
2139413.59313105404205.960679397
#Sta/Elev= 30
       0 2805.74    29.2 2793.49    72.4 2770.59   140.2  2741.8   188.6 2714.13
   268.3 2676.51     358 2644.24   374.6 2642.92   407.2 2630.91   447.4 2611.48
   480.9 2603.46   504.1 2602.14  524.082594.225     534 2592.87  544.212594.531
   557.3 2598.88     614  2601.6   650.7 2622.41   677.2 2633.08   710.9 2639.16
   744.3 2637.39   811.1 2656.89   848.2 2680.49     928 2723.11   944.7 2736.24
   958.1  2739.2   974.8 2753.04   994.9 2760.29  1004.5 2769.09  1079.4 2815.14
#Mann= 3 ,-1 , 0
       0      .1       0  524.08    .045       0  544.21      .1       0
Bank Sta=524.08,544.21
XS Rating Curve= 0 ,0
Exp/Cntr=0.3,0.1

Type RM Length L Ch R = 1 ,11797   ,352.9,352.6,352.3
XS GIS Cut Line= 2
2140467.19535455403827.2711480562139326.78753039403856.568333566
#Sta/Elev= 30
       0 2798.57    32.3 2783.04    51.9 2776.34    65.1 2767.76    78.2 2765.21
   219.3 2696.56   265.7  2678.2     285 2675.72   452.3 2621.45   478.6 2605.12
     495 2590.37   573.8 2588.24  584.612582.746   590.2 2581.87  604.842583.256
   616.4 2591.91   662.4 2603.66   691.9 2622.46   708.3 2630.28   744.4 2636.66
   790.4 2640.96   872.4 2655.66   924.9 2662.07     952 2668.51   987.3 2681.98
    1030  2704.3  1049.6 2719.51  1062.8 2721.92  1072.6 2729.78  1140.8 2767.33
#Mann= 3 ,-1 , 0
       0      .1       0  584.61    .045       0  604.84      .1       0
Bank Sta=584.61,604.84
XS Rating Curve= 0 ,0
Exp/Cntr=0.3,0.1

Type RM Length L Ch R = 1 ,11445   ,236.4,232.2,228.2
XS GIS Cut Line= 3
2140432.47331114403450.7522160562139880.17290655403514.771444976
2139385.38124523403583.130560234
#Sta/Elev= 30
       0 2795.11    73.5 2758.88    80.6 2753.14    99.9 2748.38   142.8 2719.17
   181.2 2698.89   288.2 2653.21   304.7  2641.1   321.2 2640.25   360.8  2615.5
   413.7 2592.55   440.1  2575.1  487.932568.852   499.5 2567.28  505.362569.265
   519.3 2579.47   535.9 2581.73   548.2 2591.06   578.9 2604.64   642.2  2620.3
     665 2624.63     771 2632.55   826.7 2649.37   873.6 2654.08   926.8 2668.91
   956.4 2679.51   989.6 2697.92  1002.3 2700.49    1026 2715.32  1055.5 2726.63
#Mann= 3 ,-1 , 0
       0      .1       0  487.93    .045       0  505.36      .1       0
Bank Sta=487.93,505.36
XS Rating Curve= 0 ,0
Exp/Cntr=0.3,0.1

Type RM Length L Ch R = 1 ,11213   ,180.7,193.2,201.2
XS GIS Cut Line= 4
2140312.03063864403181.6549852342139934.42640696 403245.67421414
2139731.51834822403378.0525583182139360.42460223403452.922487304
#Sta/Elev= 30
       0 2751.78    35.7 2727.88    78.3 2707.79   161.5 2673.67   201.4 2660.44
   251.4  2639.2   321.2 2616.06   331.2 2610.34   347.9  2607.8   377.8 2596.95
   404.3 2584.83   451.3 2567.85  480.792561.025   490.5 2560.75  501.662561.199
   555.9 2562.82   615.1 2591.02   664.1 2602.16   693.9 2611.47   744.4 2608.06
   780.5 2618.21   794.6 2618.22   833.4 2632.57   844.8 2633.66   874.6 2648.07
   908.4 2672.31   968.6 2704.99     982 2714.66   995.4 2717.18  1003.8 2723.06
#Mann= 3 ,-1 , 0
       0      .1       0  480.79    .045       0  501.66      .1       0
Bank Sta=480.79,501.66
XS Rating Curve= 0 ,0
Exp/Cntr=0.3,0.1

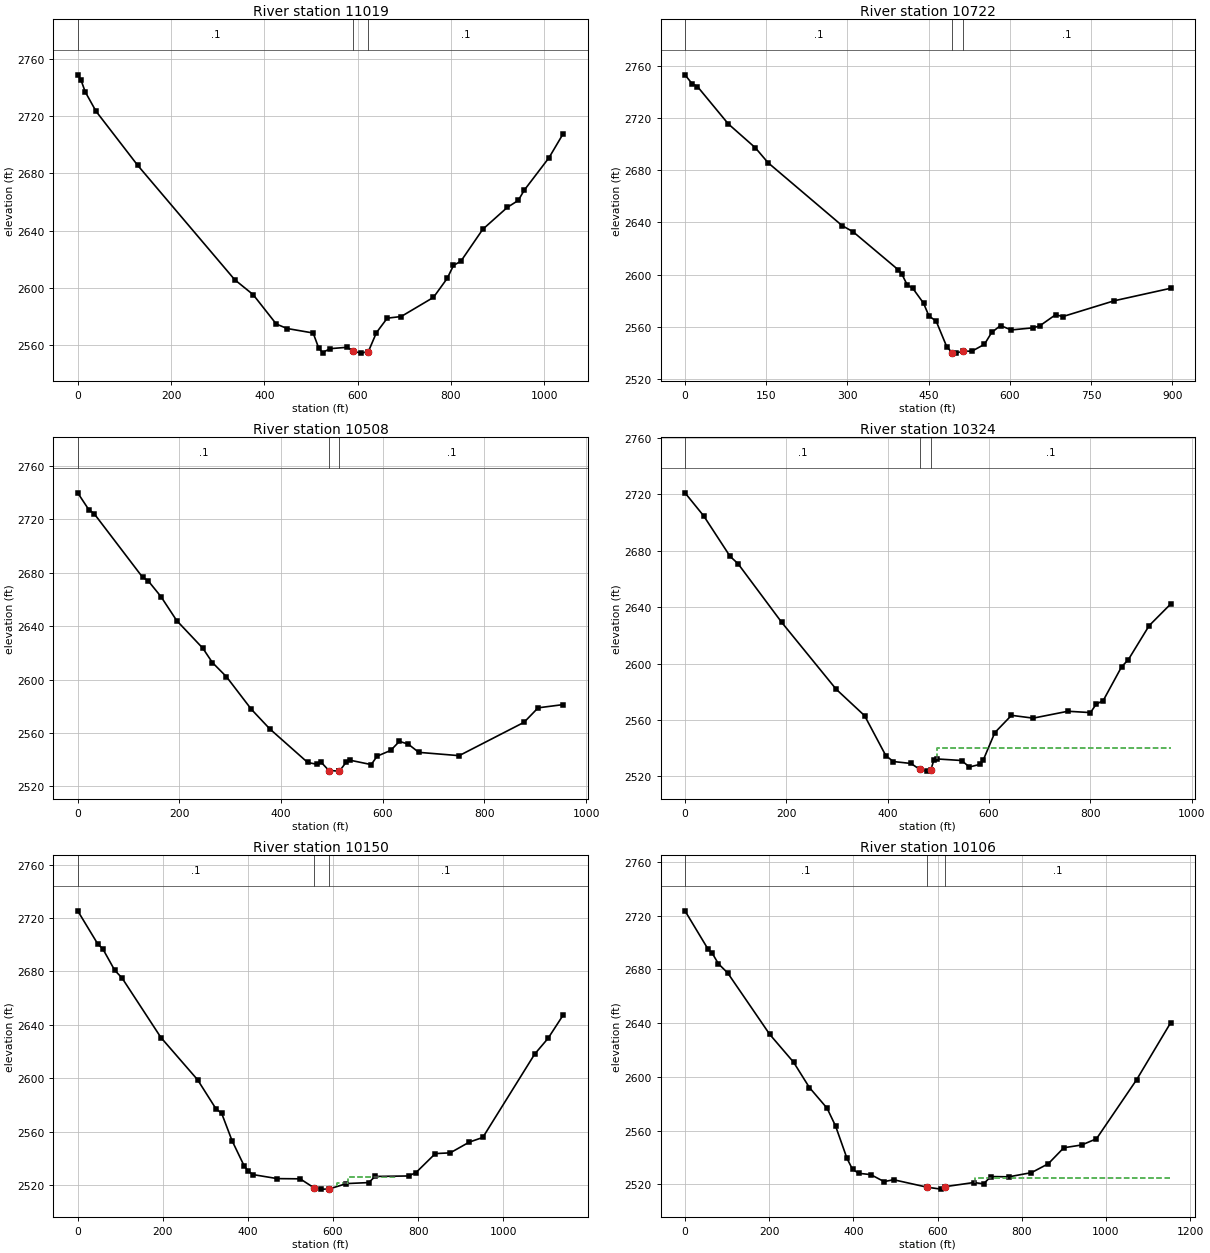
Type RM Length L Ch R = 1 ,11019   ,287.3,297,299.6
XS GIS Cut Line= 2
 2140293.5844813403130.6567276422139259.51305863403250.014428556
#Sta/Elev= 30
       0 2749.01     7.3 2745.12    16.2 2737.04    39.3  2723.5   128.5 2685.68
   336.6 2605.54   376.2 2595.06   425.7  2574.5   448.9 2571.38   504.7 2568.23
   516.5 2557.79   524.8 2554.56   541.3 2557.27   577.7 2558.23   590.6 2555.49
   607.4 2554.14   623.1 2555.26   640.4 2568.52   663.5 2578.62   693.3 2579.76
   762.6 2593.17   791.9 2606.41   805.5 2615.52   821.5 2618.56   868.3 2640.85
   921.1 2656.26   944.3 2661.03   957.2 2668.23  1010.3 2690.99  1040.9 2707.92
#Mann= 3 , 0 , 0
       0      .1       0   590.6    .045       0   623.1      .1       0
Bank Sta=590.6,623.1
XS Rating Curve= 0 ,0
Exp/Cntr=0.3,0.1

Type RM Length L Ch R = 1 ,10722   ,212,214.4,216.4
XS GIS Cut Line= 4
2140287.07399563403069.8927415612139836.77010623402984.172440559
2139713.07219088402970.0664976392139399.48718813402953.790283471
#Sta/Elev= 30
       0 2753.09    13.1  2746.3    23.1 2744.06    79.9 2715.54     130  2697.2
   153.4 2685.79   290.3 2637.57   310.4 2632.91   393.8 2603.82   400.5 2600.55
   410.5 2592.16   420.6 2589.67   440.6 2578.21   450.6 2568.38   463.9 2564.49
   483.7 2544.63  493.492540.371   500.2 2539.95  513.492541.429     530 2541.43
   553.1 2546.71   566.5 2555.79   582.8 2561.08   602.5 2557.69   643.4 2559.36
   655.1 2560.79   684.6 2569.39   697.8 2567.94   793.1 2580.08   896.9  2589.6
#Mann= 3 ,-1 , 0
       0      .1       0  493.49    .045       0  513.49      .1       0
Bank Sta=493.49,513.49
XS Rating Curve= 0 ,0
Exp/Cntr=0.3,0.1

Type RM Length L Ch R = 1 ,10508   ,185.1,184,184.8
XS GIS Cut Line= 3
2140284.90372439402933.1741829812139688.11554788402725.925909817
2139380.56102534402625.428735586
#Sta/Elev= 30
       0 2739.73      22 2727.02    32.2 2724.21   127.7 2676.52   138.4 2674.01
   163.8 2662.07   194.7 2644.17   246.3 2623.38   264.9 2612.75   292.7 2602.09
   341.6 2577.76   377.7 2563.15   452.4 2537.96   469.8 2536.66   478.3  2538.4
   494.1 2531.94  514.542531.483   514.9 2531.48   528.8 2538.47   535.8 2539.65
   577.4 2536.37   589.1 2542.69   615.7 2546.97   632.9 2553.75   650.3 2551.68
     671 2545.53   750.4 2543.06   878.1 2568.02   905.7 2578.84   955.3 2581.27
#Mann= 3 ,-1 , 0
       0      .1       0   494.1    .045       0  514.54      .1       0
Bank Sta=494.1,514.54
XS Rating Curve= 0 ,0
Exp/Cntr=0.3,0.1

Type RM Length L Ch R = 1 ,10324   ,155.9,173.7,187.8
XS GIS Cut Line= 3
2140317.46340321402847.9872423022139971.27437564402637.047691455
2139450.12960296402452.165379243
#Sta/Elev= 30
       0 2720.95      37 2704.57    89.1  2675.9   104.5 2670.82     191 2629.12
   298.2 2581.87   354.5 2563.05   396.4 2534.74   411.2 2530.57     446  2529.2
   462.9 2525.12   477.4 2523.77  485.422524.873   491.3 2531.77   497.1 2532.41
   545.9  2531.3   561.3  2526.7   581.9 2528.52   588.8 2531.73   611.5 2551.05
   644.4  2563.3   687.2 2561.31   755.8 2566.19   800.3 2565.24   811.5 2571.17
   825.5 2573.79   861.9  2597.8   874.8 2602.62   916.1 2626.85   958.4 2642.11
#Mann= 3 ,-1 , 0
       0      .1       0   462.9    .045       0  485.42      .1       0
#XS Ineff= 2 , 0
                          496.89         2539.89
Permanent Ineff=
       F       F
Bank Sta=462.9,485.42
XS Rating Curve= 0 ,0
Exp/Cntr(USF)=0,0
Exp/Cntr=0.5,0.3

Type RM Length L Ch R = 1 ,10150   ,48.6,43.9,53.2
XS GIS Cut Line= 6
2140344.60015602402833.2835147872139984.78691511402571.966635915
2139961.67042198402523.7235198152139944.58431836402362.913132817
 2139877.2449688402327.7358606612139495.32029968402192.052096632
#Sta/Elev= 30
       0 2725.38    47.6 2700.35    58.6 2697.15      87  2680.9     104 2675.22
   195.6 2630.58   281.7    2599   324.8 2577.34   338.4 2573.81   362.7 2553.45
   391.1  2534.6     401 2530.62   411.4 2528.06   469.2 2525.02   522.8 2524.86
   554.6  2518.3   572.3 2517.16   589.82517.169   631.7 2521.31   684.1 2522.06
   698.9 2526.65   777.7 2527.01   795.2  2529.6   840.5 2543.76   875.4 2544.29
   920.7  2552.4     952 2555.81    1074 2618.21  1105.4 2629.98  1141.2 2647.54
#Mann= 3 ,-1 , 0
       0      .1       0   554.6    .045       0   589.8      .1       0
#XS Ineff= 3 ,-1
       0   534.6  2521.5   609.8  634.29  2521.5  634.29     750 2526.11
Permanent Ineff=
       F       F       F
Bank Sta=554.6,589.8
XS Rating Curve= 0 ,0
Exp/Cntr(USF)=0,0
Exp/Cntr=0.5,0.3

Type RM Length L Ch R = 1 ,10106   ,301.6,286.5,255.2
XS GIS Cut Line= 5
2140361.68625963402814.1872813312139997.85275905402553.875467378
2139977.75146068402389.0448207042139965.69068165 402336.78144493
2139513.41146822402157.879889394
#Sta/Elev= 30
       0 2723.71    55.1 2694.99    65.1 2691.92    79.3 2684.31   101.5 2677.39
   201.4 2631.61   257.9 2610.93   295.5 2592.06   337.5 2576.65   357.7 2563.35
   384.9 2539.19     398 2531.06   413.1 2528.13   441.3 2527.18   472.7 2521.98
   495.8 2523.34   575.22517.793   607.7 2516.36   616.8 2518.15   685.9 2521.28
   709.3 2520.31   726.3 2525.73   769.3 2525.53     823 2528.65   862.9 2535.26
   899.8 2547.19   942.1 2549.24   977.4 2553.88  1072.7 2597.86  1153.4 2640.24
#Mann= 3 ,-1 , 0
       0      .1       0   575.2    .045       0   616.8      .1       0
#XS Ineff= 2 , 0
                          687.81         2524.93
Permanent Ineff=
       F       F
Bank Sta=575.2,616.8
XS Rating Curve= 0 ,0
Exp/Cntr(USF)=0,0
Exp/Cntr=0.5,0.3

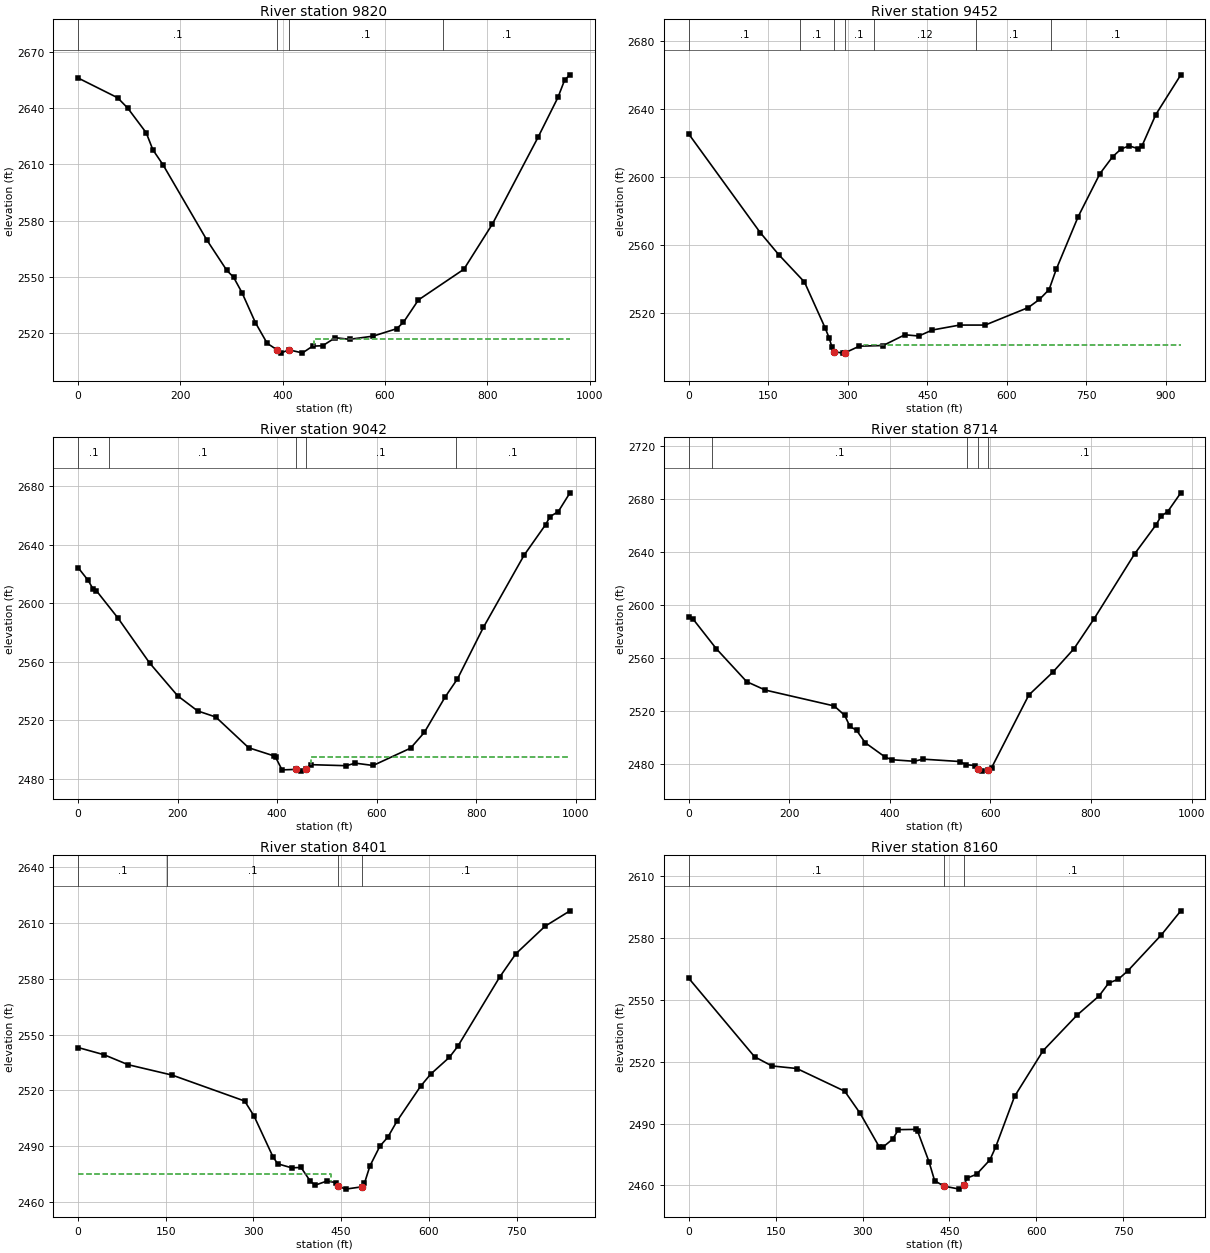
Type RM Length L Ch R = 1 ,9820    ,363.3,367.9,370
XS GIS Cut Line= 2
2140440.06876838 402167.115019562139479.78230314402115.031790391
#Sta/Elev= 30
       0 2656.17    77.4  2645.6    97.1  2640.1   133.3  2626.9   146.4 2617.78
   166.1 2609.83   251.6 2569.74     291 2553.36   304.1 2549.76   320.5 2541.55
   346.8 2525.49   369.8 2514.45  389.262510.956   396.1 2509.22  412.242510.979
   438.8 2509.32   458.5 2512.93   478.3 2513.18     503 2517.46   530.8 2516.59
   576.8 2518.29   622.8 2522.25     636 2525.61   665.5 2537.64   754.3 2554.01
   810.1 2578.17   899.1 2624.39   938.3 2645.83   951.4 2655.16   961.7 2657.84
#Mann= 4 ,-1 , 0
       0      .1       0  389.26    .045       0  412.24      .1       0
  713.56      .1       0
#XS Ineff= 2 , 0
                          460.84         2516.57
Permanent Ineff=
       F       F
Bank Sta=389.26,412.24
XS Rating Curve= 0 ,0
Exp/Cntr=0.3,0.1

Type RM Length L Ch R = 1 ,9452    ,414.8,410,404.2
XS GIS Cut Line= 3
2140468.28065422401924.0594033152140122.14322314401810.127216473
2139583.94876146401640.856229559
#Sta/Elev= 30
       0 2625.15   134.7  2567.3   169.8 2554.27   218.2 2538.24   256.9  2511.5
   264.7 2505.49     270 2500.06  274.362497.298   290.7 2496.46  294.422496.601
   321.8 2500.56   366.7 2500.93   407.7 2507.24     434 2506.52   459.5 2510.04
   511.1 2512.95   559.3 2512.95   640.7 2523.25   661.7 2528.02     680 2533.84
   693.4 2545.68   734.9 2576.71   775.9 2601.92     800 2611.93     816 2616.46
     831 2618.26   848.2  2616.6     855 2618.01   881.4 2636.66   928.6 2660.02
#Mann= 7 ,-1 , 0
       0      .1       0  209.63      .1       0  274.36    .045       0
  294.42      .1       0  348.67     .12       0  542.18      .1       0
  683.19      .1       0
#XS Ineff= 1 ,-1
  329.76  928.59 2501.09
Permanent Ineff=
       F
Bank Sta=274.36,294.42
XS Rating Curve= 0 ,0
Exp/Cntr=0.3,0.1

Type RM Length L Ch R = 1 ,9042    ,323.4,328.4,333.2
XS GIS Cut Line= 4
2140606.08418439401506.3076141482140249.09638131401445.543956146
2139981.08445014401509.5628569722139630.60680464401512.818099812
#Sta/Elev= 30
       0 2624.48    20.5  2615.6    30.5 2609.64    37.1 2608.51    80.4 2589.83
   143.6 2559.25   200.2 2536.68   240.2 2526.38   276.8 2522.18   342.7 2501.18
   393.7 2495.58     397 2494.59   409.8 2486.01  438.592486.372   447.1 2485.17
  457.252486.813   467.9 2489.59   538.7 2488.88   556.9 2490.63   592.7 2489.03
     668 2500.88   695.6 2511.62     737 2535.65   762.2 2548.29   814.2 2583.46
     896 2632.88   939.1 2653.73   948.3 2659.33   964.7 2662.74   988.2 2675.58
#Mann= 5 ,-1 , 0
       0      .1       0   61.83      .1       0  438.59    .045       0
  457.25      .1       0  759.35      .1       0
#XS Ineff= 1 ,-1
  468.02  988.16  2494.6
Permanent Ineff=
       F
Bank Sta=438.59,457.25
XS Rating Curve= 0 ,0
Exp/Cntr=0.3,0.1

Type RM Length L Ch R = 1 ,8714    ,296.1,312.8,316.3
XS GIS Cut Line= 3
2140583.29781264401326.186255232 2139943.1068358401182.957210973
2139625.18161863  401127.6184109
#Sta/Elev= 30
       0 2591.22     7.5 2589.79    54.5 2567.07     115 2542.23     152  2535.9
   289.2 2523.93     310 2516.85   320.5 2508.48   333.6 2505.63   350.7 2496.29
   390.7 2485.38   404.2 2483.43   447.9 2482.28   466.1 2483.86   538.6 2482.09
   552.1 2479.66   568.9 2479.08  574.682476.689   582.3 2474.85  594.832475.709
   602.5 2477.58   676.3 2532.16   723.8 2549.26   766.1    2567   806.2 2589.61
     887 2638.57   929.4 2660.34   939.4 2666.85   952.7 2670.34   978.7 2684.44
#Mann= 5 ,-1 , 0
       0      .1       0   45.51      .1       0  553.33      .1       0
  574.68    .045       0  594.83      .1       0
Bank Sta=574.68,594.83
XS Rating Curve= 0 ,0
Exp/Cntr=0.3,0.1

Type RM Length L Ch R = 1 ,8401    ,254.8,240.7,230.9
XS GIS Cut Line= 4
2140437.89849713401150.4051107322140199.18342339401019.111738145
2139948.53234988400842.2452939752139706.56170522400741.333750397
#Sta/Elev= 30
       0    2543    44.6  2539.1    85.7 2533.74   161.3 2528.12     285 2514.19
   301.1  2506.1   333.2 2484.33   341.3 2480.43   365.3 2478.24   381.4 2478.43
   397.5 2470.97   405.5 2468.89   425.6 2471.11   441.6 2470.25   445.42468.329
   457.7 2466.77  484.922467.986   489.8 2469.81   499.2 2479.19   516.3  2489.9
     530 2494.79   545.5 2503.35   585.9 2522.14   603.2 2528.68   635.2 2537.73
   649.4 2543.59   721.4 2581.02   748.9 2593.47   798.7 2608.25   841.4 2616.57
#Mann= 4 ,-1 , 0
       0      .1       0  151.74      .1       0   445.4    .045       0
  484.92      .1       0
#XS Ineff= 2 , 0
          432.37 2475.08
Permanent Ineff=
       F       F
Bank Sta=445.4,484.92
XS Rating Curve= 0 ,0
Exp/Cntr=0.3,0.1

Type RM Length L Ch R = 1 ,8160    ,255,261.7,267.6
XS GIS Cut Line= 4
2140570.27716939400740.2487788052140191.58796614 400687.08024998
 2139952.8725643400700.1012213082139728.26310539400659.953663811
#Sta/Elev= 30
       0 2560.32   113.5 2522.34   143.3  2517.9   186.4 2516.65   269.2 2505.64
   295.7 2494.97   328.8 2478.67   335.4 2478.61     352 2482.44   361.9 2487.02
   391.7 2487.15     395 2486.31   414.7 2471.51   424.5 2462.22     441 2459.63
   467.3  2458.2  475.182460.089   480.4 2463.56   496.8 2465.37   519.8 2472.33
   529.7 2478.48   562.5 2503.15   611.8  2525.3   670.3 2542.48   708.5 2551.84
     725 2558.05   741.7 2559.92   758.3 2564.04   815.7 2581.31   849.6 2593.06
#Mann= 3 , 0 , 0
       0      .1       0     441    .045       0  475.18      .1       0
Bank Sta=441,475.18
XS Rating Curve= 0 ,0
Exp/Cntr=0.3,0.1