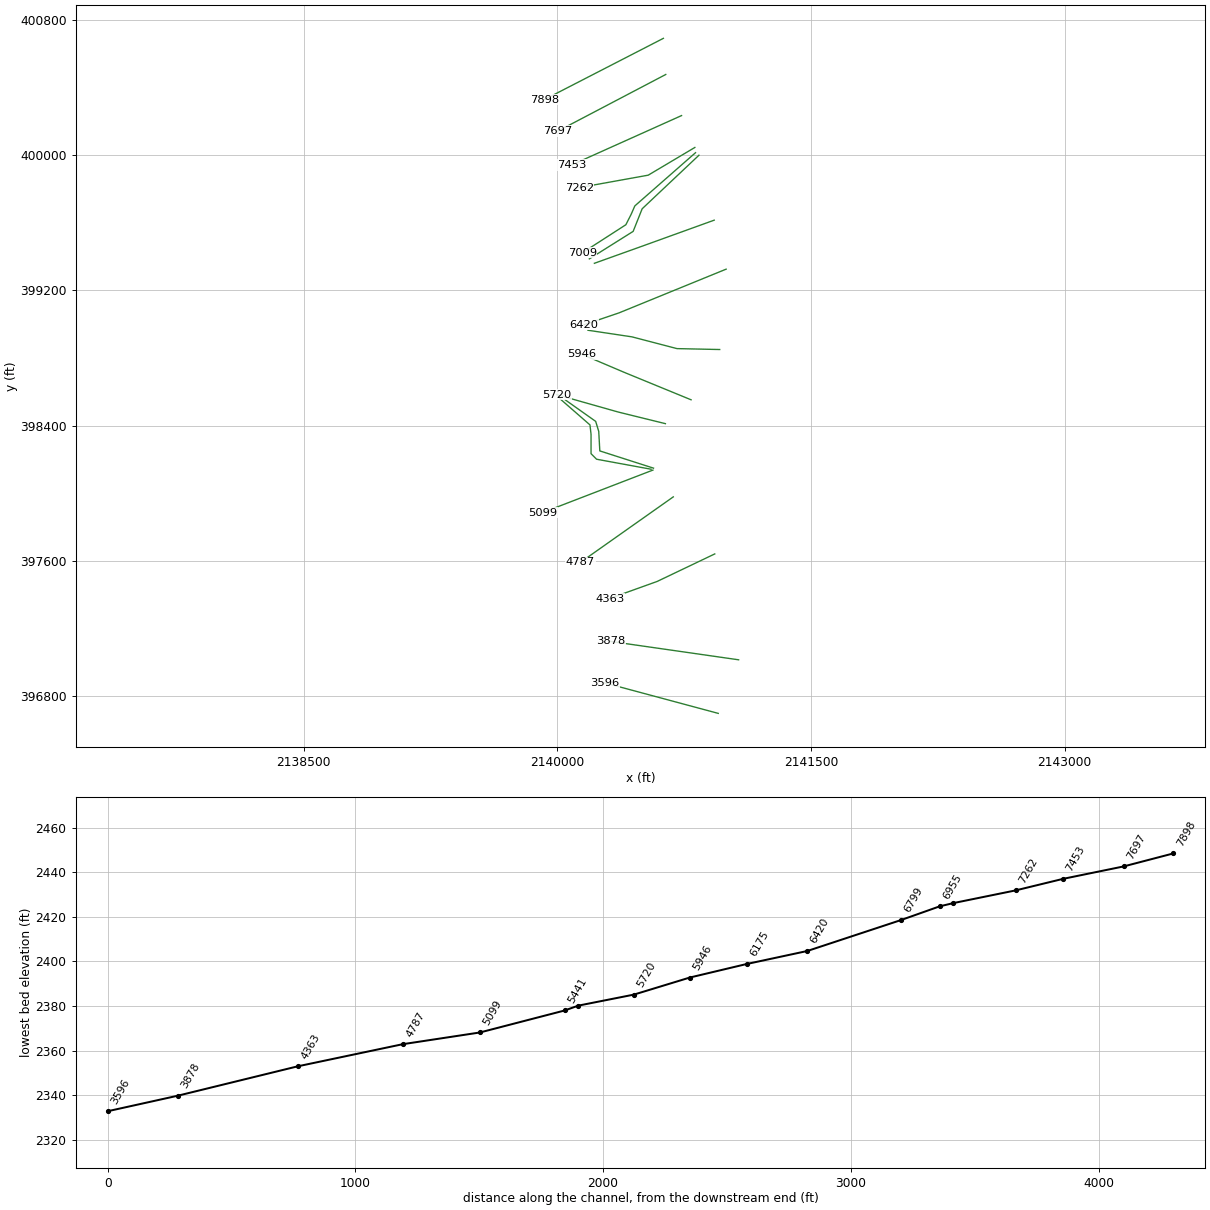
HEC-RAS study PNTHRCMPCK.prj: PNTHRCMPCK

--- PNTHRCMPCK.g01 (geometry) --- (continued)

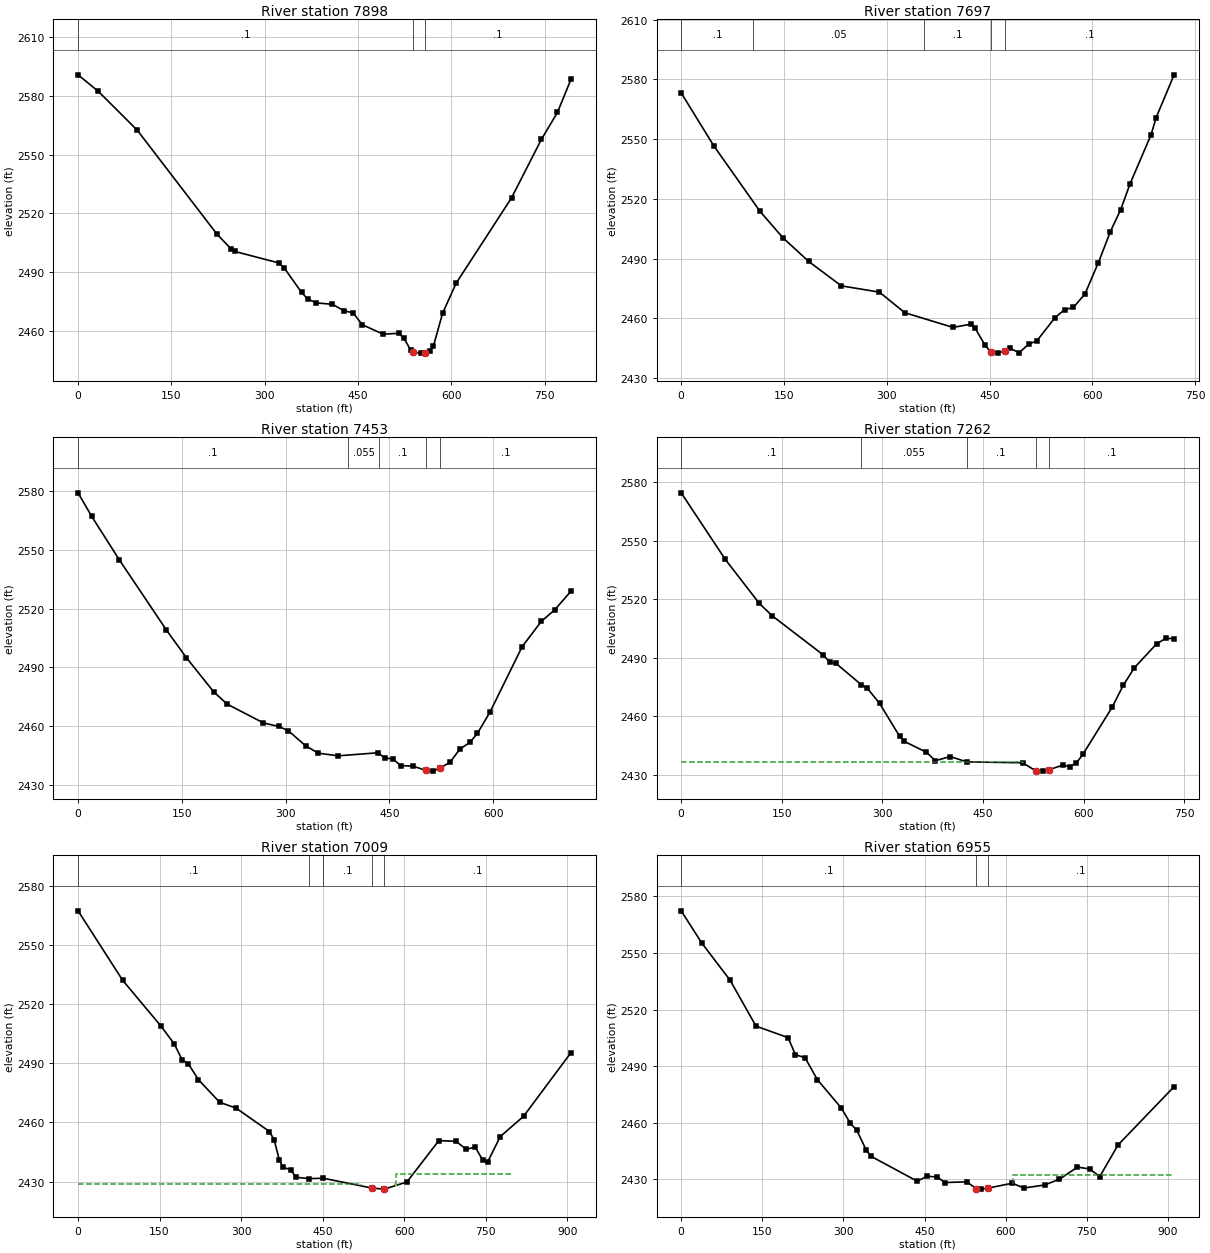
Type RM Length L Ch R = 1 ,7898    ,200.8,201.2,201
XS GIS Cut Line= 2
2140627.78558455400690.3354928052139923.57570688400327.922503725
#Sta/Elev= 30
       0 2590.76    32.4 2582.34    95.1 2562.45   222.7 2509.47   246.4 2501.53
   251.9 2500.43   322.6 2494.55   331.3 2491.97   359.1 2479.49   368.9 2476.13
   382.9 2474.12   408.7  2473.4   427.3 2470.11     442    2469   456.7 2462.97
   489.9 2458.16     515 2458.53   523.1 2456.29   534.2 2450.16  537.922448.917
   551.6 2448.43  557.962448.541   566.2 2449.66   571.1 2452.11   585.7 2468.78
   607.6 2484.23   696.5 2527.82   744.5 2557.73   770.3 2571.52     792 2588.43
#Mann= 3 ,-1 , 0
       0      .1       0  537.92    .045       0  557.96      .1       0
Bank Sta=537.92,557.96
XS Rating Curve= 0 ,0
Exp/Cntr=0.3,0.1

Type RM Length L Ch R = 1 ,7697    ,244.3,244.1,243.1
XS GIS Cut Line= 2
2140641.89152747400476.5767339772140004.95579347400142.375630721
#Sta/Elev= 30
       0 2573.25    47.5 2546.71   115.1 2513.75   148.5  2500.5   186.1  2488.6
   233.7 2476.37   289.3 2473.21   326.3 2462.89   396.7  2455.5   422.7 2457.12
   429.1 2455.05   443.6 2446.44  452.48 2443.02   462.4 2442.59  472.592443.884
   480.1 2444.96   493.1 2442.83   507.9 2447.24   518.9 2448.68   545.7 2460.47
   559.7 2464.44   572.4 2465.51   589.4 2472.37   608.9 2488.05   626.4 2503.64
   641.3 2514.55     655 2527.51   685.7  2552.2   693.1 2560.77   719.3  2582.3
#Mann= 5 ,-1 , 0
       0      .1       0   105.4     .05       0  353.83      .1       0
  452.48    .045       0  472.59      .1       0
Bank Sta=452.48,472.59
XS Rating Curve= 0 ,0
Exp/Cntr=0.3,0.1

Type RM Length L Ch R = 1 ,7453    ,193.1,190.8,188.3
XS GIS Cut Line= 2
2140735.20761381400233.5214458112140085.25090846399941.637515143
#Sta/Elev= 30
       0 2579.07    19.8 2566.99    59.4 2545.01   127.7 2509.05   156.5 2494.98
   195.9 2477.56   215.7 2471.19     268 2461.64   290.2 2459.82     304 2457.63
   329.1 2449.92   347.1 2446.22   375.9 2444.84   433.4  2446.4   444.1 2443.64
     455 2443.31   466.4 2439.83   483.8 2439.63  502.972437.352   512.6 2437.03
  523.052438.505   537.7 2441.56   552.1 2448.33   566.5 2451.69   577.3 2456.32
   595.5 2467.18     642 2500.58   669.9 2513.56   688.8 2519.26   712.5 2528.84
#Mann= 5 ,-1 , 0
       0      .1       0  389.96    .055       0  435.27      .1       0
  502.97    .045       0  523.05      .1       0
Bank Sta=502.97,523.05
XS Rating Curve= 0 ,0
Exp/Cntr=0.3,0.1

Type RM Length L Ch R = 1 ,7262    ,243.5,253,262.4
XS GIS Cut Line= 3
2140813.90729576400045.0615176012140538.16932079399881.150610262
2140130.68986891399807.620483605
#Sta/Elev= 30
       0 2574.61    65.8 2540.45   116.4 2517.93   135.5 2511.59   211.9 2491.45
   221.4 2487.77     231 2487.08   268.6 2476.17   276.7  2474.7   295.8 2466.62
   325.6 2449.77   332.3 2447.17   365.7 2441.54     379 2437.22   401.2 2439.35
   425.7 2436.61     509 2436.17   528.62432.018     539 2431.87   548.62432.614
     569 2434.96     579 2434.16     589 2435.94   598.9  2440.5   642.4 2464.57
     659 2475.84   675.7 2484.92   708.8 2497.16   722.4 2499.94   734.8 2499.85
#Mann= 5 ,-1 , 0
       0      .1       0   268.6    .055       0   425.7      .1       0
   528.6    .045       0   548.6      .1       0
#XS Ineff= 2 , 0
          508.96 2436.68
Permanent Ineff=
       F       F
Bank Sta=528.6,548.6
XS Rating Curve= 0 ,0
Exp/Cntr(USF)=0,0
Exp/Cntr=0.5,0.3

Type RM Length L Ch R = 1 ,7009    ,53.7,54.7,55.4
XS GIS Cut Line= 5
 2140817.8716419400014.0664245872140459.06346591399699.481105021
 2140436.9520377399649.2278590842140405.79502522399587.918899041
2140148.49840602399422.083187449
#Sta/Elev= 30
       0 2567.18    82.2 2531.92   151.9 2508.99   176.8 2499.83   191.7  2491.6
   202.8 2489.72   221.5  2481.6   260.6 2470.16   291.1 2467.15   352.2 2455.33
   360.9 2451.06   370.2 2441.08   377.2 2437.12   391.1 2436.08   400.7 2432.16
   425.6 2431.46   451.6 2431.65   541.22426.657   562.7 2426.15   563.6 2426.14
   605.2 2429.77   663.8 2450.71   695.5 2450.39   714.2 2446.34   730.8 2447.42
     745 2440.68   753.5 2439.81     777  2452.8   819.9 2463.07     907 2495.29
#Mann= 5 ,-1 , 0
       0      .1       0   425.6    .055       0   451.6      .1       0
   541.2    .045       0   562.7      .1       0
#XS Ineff= 3 ,-1
       0   521.2  2428.9   582.7  584.31  2428.9  584.31     800 2433.92
Permanent Ineff=
       F       F       F
Bank Sta=541.2,562.7
XS Rating Curve= 0 ,0
Exp/Cntr(USF)=0,0
Exp/Cntr=0.5,0.3

Type RM Length L Ch R = 1 ,6955    ,162.7,156,147
XS GIS Cut Line= 4
2140837.97294027399998.9904508062140502.28125742399682.395001403
2140449.01281672399548.7213672112140189.70606769399385.900850375
#Sta/Elev= 30
       0 2572.38    37.9 2555.37    90.5 2535.54   138.3 2511.21   197.7 2505.07
   211.2 2496.08   229.2 2494.37   251.8 2482.82   296.1 2467.74   312.8 2459.62
   324.8 2455.96     342  2445.5     351 2442.12   436.7 2428.88   454.3 2431.54
   473.5 2431.11   487.7  2428.2   528.1 2428.55   546.12424.869   554.8 2424.69
   567.22425.226   612.4 2427.82   633.6 2425.28   671.9 2426.87   699.4 2429.93
   732.9 2436.36   755.2 2435.41   774.2 2431.39   807.9 2448.14   911.5 2479.05
#Mann= 3 ,-1 , 0
       0      .1       0   546.1    .045       0   567.2      .1       0
#XS Ineff= 2 , 0
                          614.04         2432.26
Permanent Ineff=
       F       F
Bank Sta=546.1,567.2
XS Rating Curve= 0 ,0
Exp/Cntr(USF)=0,0
Exp/Cntr=0.5,0.3

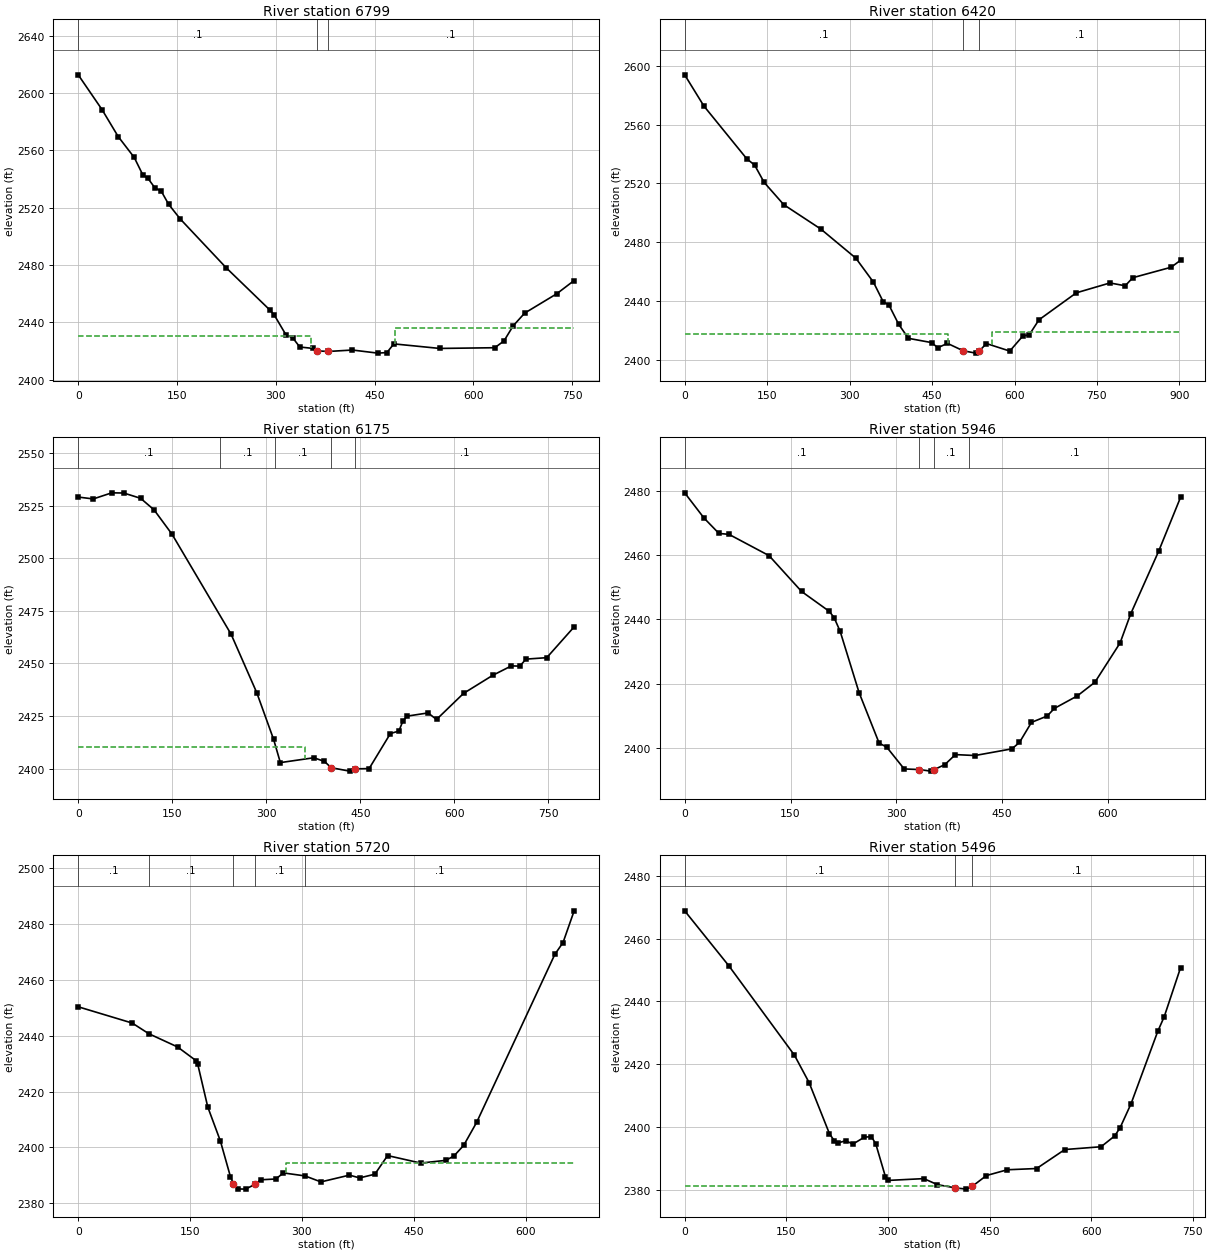
Type RM Length L Ch R = 1 ,6799    ,373.1,378.3,381.5
XS GIS Cut Line= 3
2140928.34994406399615.0318691432140510.59815489399464.207039565
2140219.79952389399360.040253147
#Sta/Elev= 30
       0 2612.62    36.2 2588.34    60.7 2569.56    85.1 2554.97    98.1 2542.84
     106 2540.38     116 2534.04   126.3  2531.3   137.4 2522.26   154.8 2512.16
   224.6 2478.11   290.9 2448.66   297.8 2445.02   315.3  2431.4   325.8 2429.17
   336.4 2422.82   357.1 2421.81   362.52420.126  379.482419.709   416.4 2420.71
   454.8 2418.55   468.7 2418.94   479.2    2425   548.9 2421.82   632.5 2422.32
   646.5 2427.08   660.4 2437.57   677.8 2446.43   726.6 2459.96     753 2469.19
#Mann= 3 ,-1 , 0
       0      .1       0   362.5    .045       0  379.48      .1       0
#XS Ineff= 2 , 0
          354.12 2430.79  481.27          2435.8
Permanent Ineff=
       F       F
Bank Sta=362.5,379.48
XS Rating Curve= 0 ,0
Exp/Cntr=0.3,0.1

Type RM Length L Ch R = 1 ,6420    ,258.2,245.3,236.8
XS GIS Cut Line= 3
2140998.87933056399325.3182097232140366.28413905399067.071678981
2140159.03586589398996.542292476
#Sta/Elev= 30
       0 2593.86      35 2572.63     113 2536.76   127.2 2532.53   144.6 2520.72
   180.3 2505.58   247.7 2489.01   311.4 2469.22   343.3 2452.96     361 2439.73
   371.7  2437.3   389.4  2424.2   407.1 2414.73   449.6 2411.81   460.3 2408.32
     478 2411.32  506.74 2406.27   529.6 2404.68  536.162406.175   548.9  2411.2
   591.4 2406.08   615.2 2416.35   626.8 2417.11   644.5 2427.32   712.5 2445.68
   773.6 2452.38   801.4 2450.47   815.2 2455.95   884.8 2463.04   902.2 2467.84
#Mann= 3 ,-1 , 0
       0      .1       0  506.74    .045       0  536.16      .1       0
#XS Ineff= 2 , 0
          478.78 2417.59  559.71         2418.84
Permanent Ineff=
       F       F
Bank Sta=506.74,536.16
XS Rating Curve= 0 ,0
Exp/Cntr=0.3,0.1

Type RM Length L Ch R = 1 ,6175    ,230.4,228.5,226.9
XS GIS Cut Line= 4
2140960.90204431398850.0576773142140708.08069955398855.483191401
2140442.23871155398924.9276063142140181.82223764 398963.99019222
#Sta/Elev= 30
       0 2529.01      24 2528.12    53.5 2531.02    72.6 2530.93    99.5 2528.42
   120.9 2522.96   149.7 2511.32   243.9 2463.82   284.8 2436.07   311.7 2413.86
   322.4 2402.88   375.8 2405.18   392.8 2403.44  403.342400.469   432.7 2398.83
  441.752399.905     464 2400.04   497.9 2416.68   511.4 2417.86   518.2 2422.86
     525 2424.97     558 2426.48   571.5 2423.37   614.6 2435.76   661.1 2444.33
   690.9 2448.82   704.2  2448.7   714.2 2452.03   747.3 2452.72     791 2467.36
#Mann= 5 ,-1 , 0
       0      .1       0  226.37      .1       0  314.38      .1       0
  403.34    .045       0  441.75      .1       0
#XS Ineff= 2 , 0
          361.74 2410.35
Permanent Ineff=
       F       F
Bank Sta=403.34,441.75
XS Rating Curve= 0 ,0
Exp/Cntr=0.3,0.1

Type RM Length L Ch R = 1 ,5946    ,224.8,226.4,227.5
XS GIS Cut Line= 3
2140791.63105738398552.7488887312140397.75093964398714.424090311
2140142.75965172398822.931091145
#Sta/Elev= 30
       0 2479.31    27.4 2471.47    48.6 2466.68    62.8  2466.4   119.6 2459.78
   165.7 2448.64   205.2 2442.42   211.8 2440.49   220.3 2436.29   247.2 2417.19
   275.6  2401.5   286.3 2400.27   311.1 2393.47   332.82393.278   348.5 2392.79
  352.872393.208   368.6 2394.79   383.7 2397.93   411.4 2397.64   463.8 2399.72
   474.5 2401.71   491.5 2407.94   513.7 2409.92     524 2412.29   556.5 2416.18
   581.4 2420.42   617.1 2432.64     632  2441.6   671.6 2461.07   702.9 2477.96
#Mann= 4 ,-1 , 0
       0      .1       0   332.8    .045       0  352.87      .1       0
  402.73      .1       0
Bank Sta=332.8,352.87
XS Rating Curve= 0 ,0
Exp/Cntr=0.3,0.1

Type RM Length L Ch R = 1 ,5720    ,243.9,223.9,210.4
XS GIS Cut Line= 3
2140639.72158431398411.6897876412140361.94359656398480.049230978
2139997.36033621398583.130717725
#Sta/Elev= 30
       0 2450.27    72.4 2444.46    94.6 2440.66   133.2 2435.92   158.1    2431
   160.2  2429.8   173.7 2414.46   190.6 2402.32   204.1 2389.56  208.05 2387.04
   214.3 2385.19   224.4 2385.12   237.3 2386.87   244.7 2388.46   264.9 2388.74
   275.1 2390.91   304.1 2389.84   325.4  2387.7   363.6 2390.12   377.3 2389.13
   397.7 2390.45   414.8 2397.11   459.1 2394.43   492.9  2395.4   503.8 2396.98
   516.8 2400.75   534.1 2408.94     639    2469     650 2473.23   664.9 2484.56
#Mann= 5 ,-1 , 0
       0      .1       0    94.6      .1       0  208.05    .045       0
   237.3      .1       0   304.1      .1       0
#XS Ineff= 2 , 0
                          278.89         2394.32
Permanent Ineff=
       F       F
Bank Sta=208.05,237.3
XS Rating Curve= 0 ,0
Exp/Cntr=0.5,0.3

Type RM Length L Ch R = 1 ,5496    ,54.9,55.4,54.2
XS GIS Cut Line= 5
2140569.53596243398148.5328187022140251.86946104398250.477369293
2140245.49792663398366.0752079092140227.29354259398425.239456019
2140047.07014066398552.670144257
#Sta/Elev= 30
       0  2468.9    65.5 2451.29     162 2422.88   183.6 2414.17   213.7 2397.85
   220.6 2395.67   226.5 2394.92   237.8 2395.63   248.2 2394.54   265.4 2396.77
   275.7  2396.9     282 2394.64   296.4 2384.09   299.8 2382.96     353 2383.54
   373.1 2381.61   399.4 2380.59   415.9 2380.19   424.6 2381.11   445.4 2384.52
   476.1 2386.36   519.5 2386.76   561.1 2392.81   614.6  2393.7   634.7 2397.14
   642.7 2399.78   658.8 2407.39   698.3 2430.51   707.8 2435.15     732 2450.83
#Mann= 3 ,-1 , 0
       0      .1       0   399.4    .045       0   424.6      .1       0
#XS Ineff= 2 , 0
           389.4  2381.3   434.6          2381.3
Permanent Ineff=
       F       F
Bank Sta=399.4,424.6
XS Rating Curve= 0 ,0
Exp/Cntr(USF)=0,0
Exp/Cntr=0.5,0.3

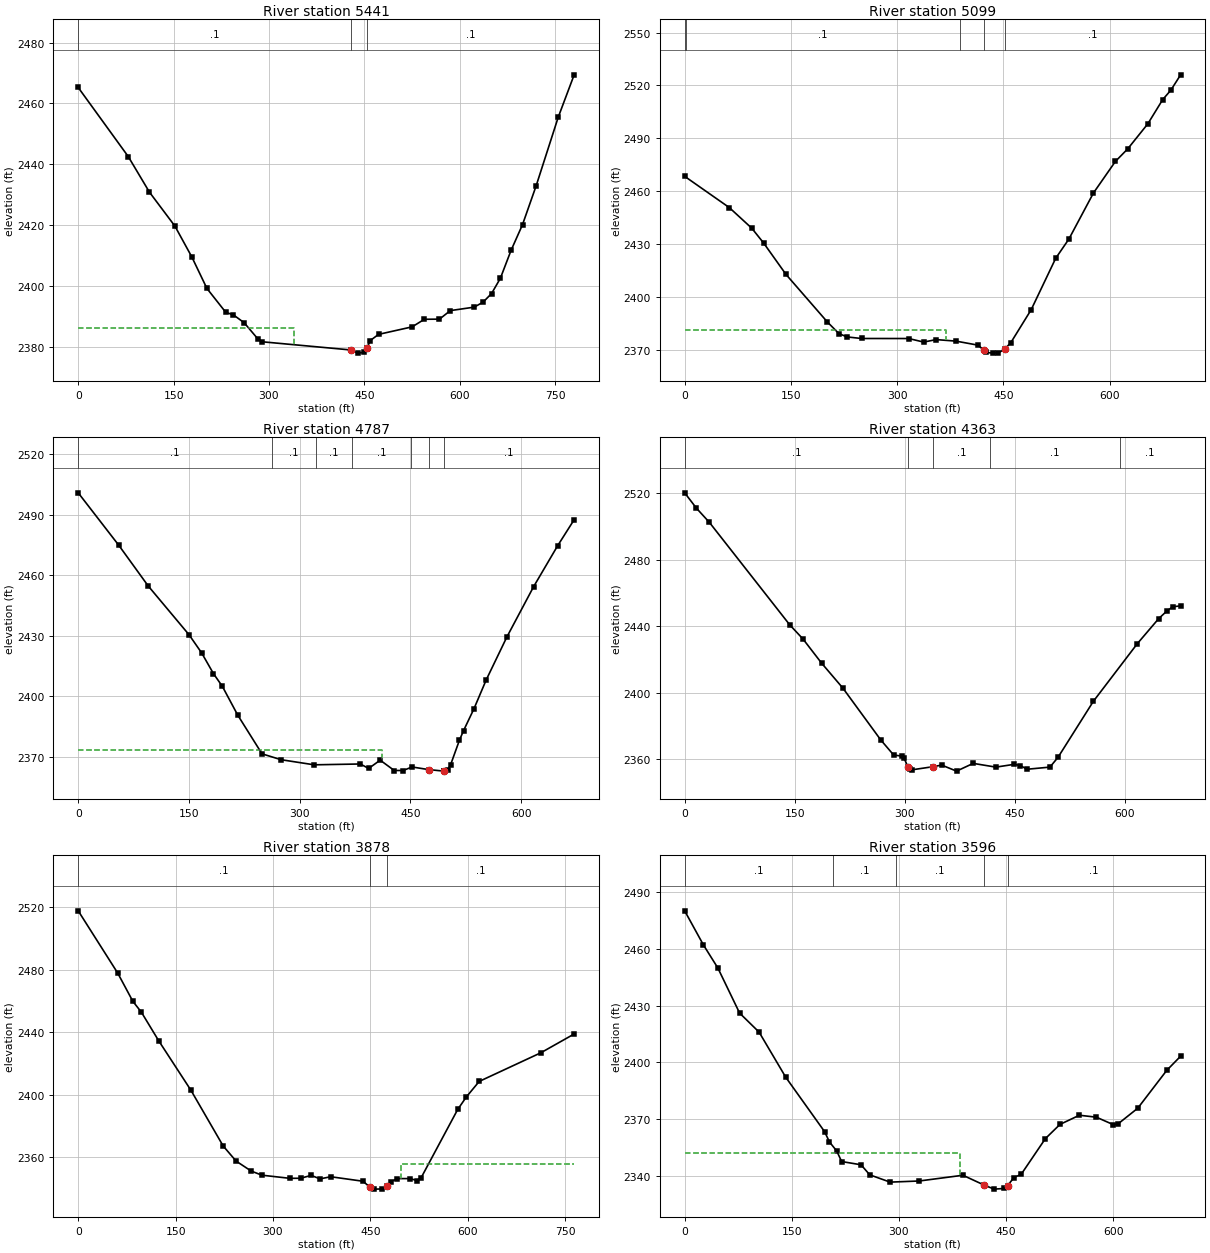
Type RM Length L Ch R = 1 ,5441    ,319.8,342,363.1
XS GIS Cut Line= 6
2140554.97245521 398142.16128429 2140232.7548578398201.325532401
2140199.98696654398234.0934236622140199.98696654398348.781043076
2140193.61543213 398404.30441438 2140016.1226878398559.041678669
#Sta/Elev= 30
       0 2465.24    78.7 2442.56     112 2430.88   152.1 2419.72   178.7 2409.59
   202.4 2399.26   232.1  2391.4   244.1 2390.57     261 2387.99   282.1 2382.79
   289.2 2381.74   429.8 2379.03   439.6 2378.01   449.5 2378.27     454 2379.59
   459.3 2382.14   472.4 2384.17   525.2 2386.64   544.5 2389.13   568.2 2389.17
   585.2 2391.97   622.7 2393.11   636.6 2394.72   650.1 2397.57     664 2402.61
   680.7 2411.72   698.8 2420.21   720.3    2433   754.9 2455.45     780  2469.4
#Mann= 3 ,-1 , 0
       0      .1       0   429.8    .045       0     454      .1       0
#XS Ineff= 2 , 0
          339.86 2386.42
Permanent Ineff=
       F       F
Bank Sta=429.8,454
XS Rating Curve= 0 ,0
Exp/Cntr(USF)=0,0
Exp/Cntr=0.5,0.3

Type RM Length L Ch R = 1 ,5099    ,308.8,311.4,314.5
XS GIS Cut Line= 2
2140565.93662688398137.167042732 2139912.7250068 397885.43099764
#Sta/Elev= 30
       0 2468.42      63  2450.7    94.7    2439   111.5 2430.57     143 2412.79
   201.4 2385.81   217.7 2379.23   229.3 2377.33   249.6 2376.45   316.2 2376.43
   337.3 2374.42   354.9 2375.82     383 2374.96   414.6 2372.63  421.89 2369.78
   425.2 2368.57   434.9 2368.15   442.8 2368.31  451.432370.339   460.3 2374.07
   489.1  2392.8   523.7 2421.95   542.3 2432.85     577 2459.01     608 2476.91
   625.3 2483.99   653.7 2498.21   674.8    2512   686.2 2517.29     700    2526
#Mann= 5 ,-1 , 0
       0      .1       0     1.2      .1       0  388.26      .1       0
  421.89    .045       0  451.43      .1       0
#XS Ineff= 2 , 0
          368.53 2381.26
Permanent Ineff=
       F       F
Bank Sta=421.89,451.43
XS Rating Curve= 0 ,0
Exp/Cntr=0.3,0.1

Type RM Length L Ch R = 1 ,4787    ,422.3,424.7,408.2
XS GIS Cut Line= 2
2140686.37962747397978.7470839772140137.33446573397591.377123818
#Sta/Elev= 30
       0 2500.92    54.8 2474.99    94.9 2454.69   150.2 2430.51   167.2 2421.55
   183.2 2411.27   195.3 2404.93   216.1 2390.69     249 2371.48   274.9 2368.56
   319.7 2366.03   382.2 2366.44   393.5 2364.23   409.1 2368.34   428.2 2363.21
   440.2 2363.21   452.3 2364.96  474.642363.667  495.012362.909     496  2362.9
   500.4 2363.39   504.5 2366.05   516.5 2378.25   522.1 2383.01   536.3 2393.95
   552.7 2408.11   580.7 2429.39   616.9 2454.33   649.6 2474.72   671.9  2487.6
#Mann= 7 ,-1 , 0
       0      .1       0  261.89      .1       0  322.39      .1       0
  371.25      .1       0  451.43      .1       0  474.64    .045       0
  495.01      .1       0
#XS Ineff= 2 , 0
          411.21 2373.47
Permanent Ineff=
       F       F
Bank Sta=474.64,495.01
XS Rating Curve= 0 ,0
Exp/Cntr=0.3,0.1

Type RM Length L Ch R = 1 ,4363    ,487.7,484.4,467.1
XS GIS Cut Line= 3
2140931.60518689397641.2904098032140590.89326988397478.529908568
2140309.86036739397377.618364975
#Sta/Elev= 30
       0  2520.3    15.9 2511.13    33.6 2502.57   143.2 2440.95   161.4 2432.36
   186.8 2417.83   215.9 2402.77   267.4 2371.69     285 2362.61   295.9 2362.03
   299.1 2360.78  304.54 2355.37   306.8 2353.96   310.4 2353.78  338.532355.618
   350.4 2356.59   370.7 2352.96   393.4 2357.62   424.3 2355.37   449.2 2357.03
   457.7 2356.34   466.6 2354.08     498 2355.38     509 2361.23   557.2 2394.92
   617.2 2429.62   646.3 2444.66   657.7 2449.34   665.4 2451.76   676.2 2452.35
#Mann= 5 ,-1 , 0
       0      .1       0  304.54    .045       0  338.53      .1       0
  415.88      .1       0  593.24      .1       0
Bank Sta=304.54,338.53
XS Rating Curve= 0 ,0
Exp/Cntr=0.3,0.1

Type RM Length L Ch R = 1 ,3878    ,284.1,282.3,281.1
XS GIS Cut Line= 2
2141072.66428797397015.2053758952140316.37085305397123.712376729
#Sta/Elev= 30
       0 2517.51    60.9 2477.72    84.1 2459.77    97.4 2452.72   123.9 2434.59
   173.7 2402.88   223.3 2367.34   243.2  2357.7   266.4 2351.34     283 2348.68
   326.1 2346.68   342.6 2346.72   358.9 2348.56   372.5 2346.32     389 2347.69
   438.8 2344.81  449.242341.063   455.3 2339.78   468.6 2339.89  476.192341.659
   481.8 2344.58   491.8 2346.51   511.7  2346.5   521.6 2345.25   528.2 2346.99
   584.6 2390.65   597.8 2398.58   617.7 2408.56   712.8 2426.88     764 2438.85
#Mann= 3 ,-1 , 0
       0      .1       0  449.24    .045       0  476.19      .1       0
#XS Ineff= 2 , 0
                          497.57         2355.59
Permanent Ineff=
       F       F
Bank Sta=449.24,476.19
XS Rating Curve= 0 ,0
Exp/Cntr=0.3,0.1

Type RM Length L Ch R = 1 ,3596    ,430.1,431.5,432.2
XS GIS Cut Line= 2
2140952.22161546396698.3651303052140281.64848155396878.486489221
#Sta/Elev= 30
       0 2480.25    26.2 2462.21    46.4    2450    76.9 2426.09   104.2 2415.99
   141.5  2392.1   195.9 2363.27   202.7 2357.81   212.9 2353.03   219.7 2347.46
   246.9 2345.73   259.1 2340.41   287.6 2336.55   328.4 2337.15   389.5 2340.19
  419.232334.988   433.2 2332.84   447.3 2333.19  451.982334.626   460.9 2338.98
   471.1 2340.68     505 2359.61   525.4 2367.12   552.6 2371.98   576.4 2370.94
   600.2 2366.97   606.9 2367.46   634.3  2375.7   674.9 2395.75   694.3 2403.25
#Mann= 5 ,-1 , 0
       0      .1       0  207.71      .1       0  296.05      .1       0
  419.23    .045       0  451.98      .1       0
#XS Ineff= 2 , 0
          385.06 2352.11
Permanent Ineff=
       F       F
Bank Sta=419.23,451.98
XS Rating Curve= 0 ,0
Exp/Cntr=0.3,0.1