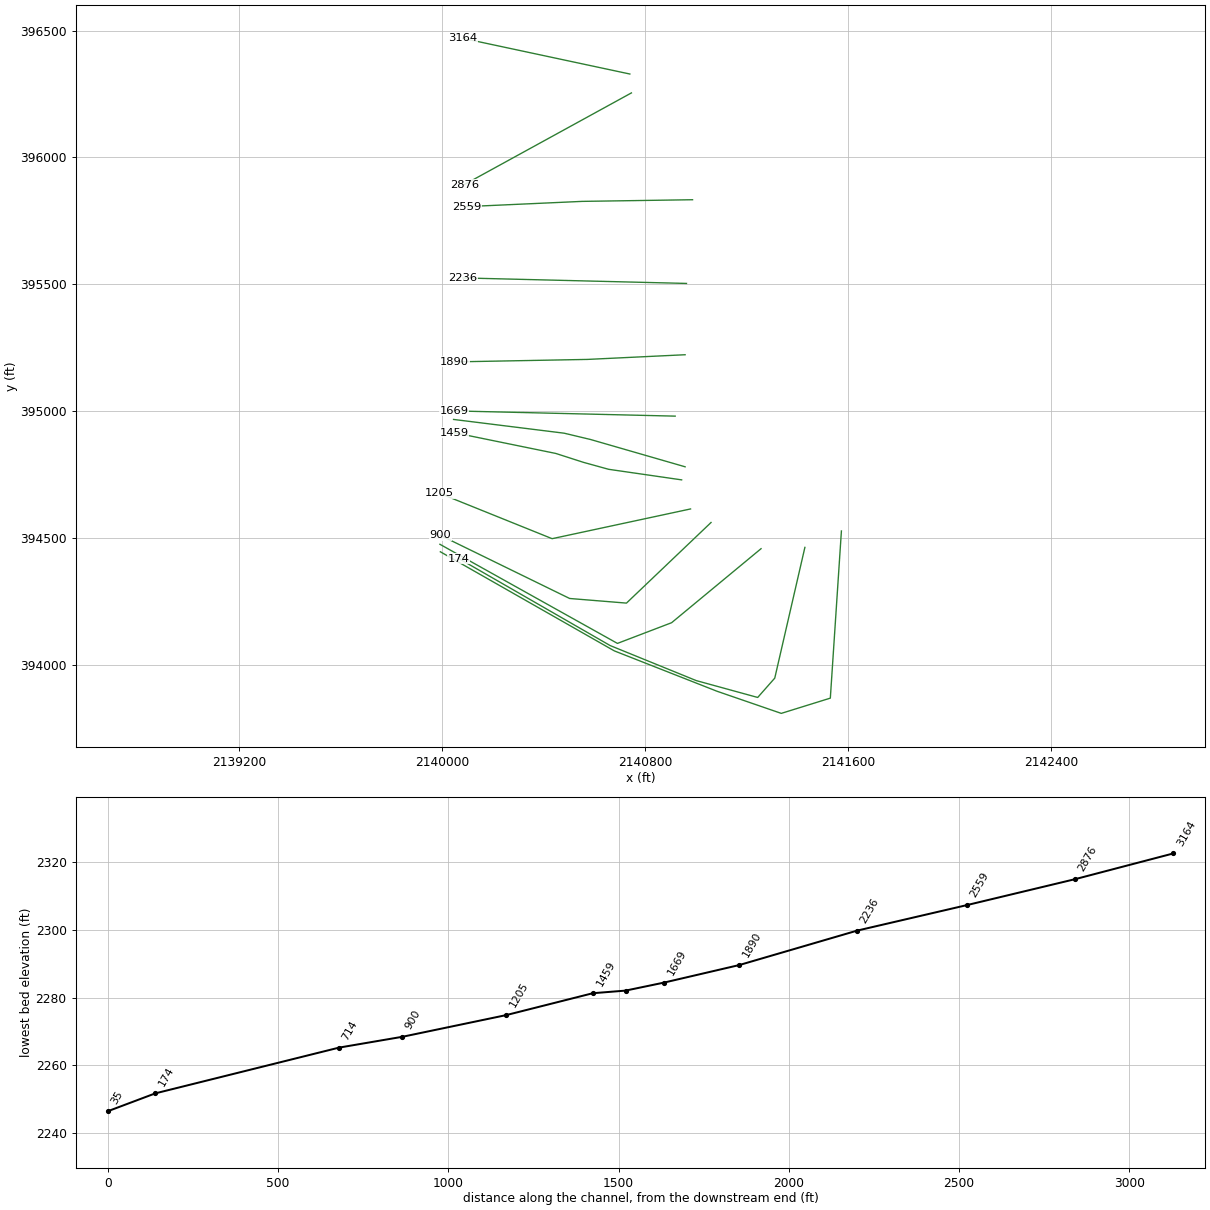
HEC-RAS study PNTHRCMPCK.prj: PNTHRCMPCK

--- PNTHRCMPCK.g01 (geometry) --- (continued)

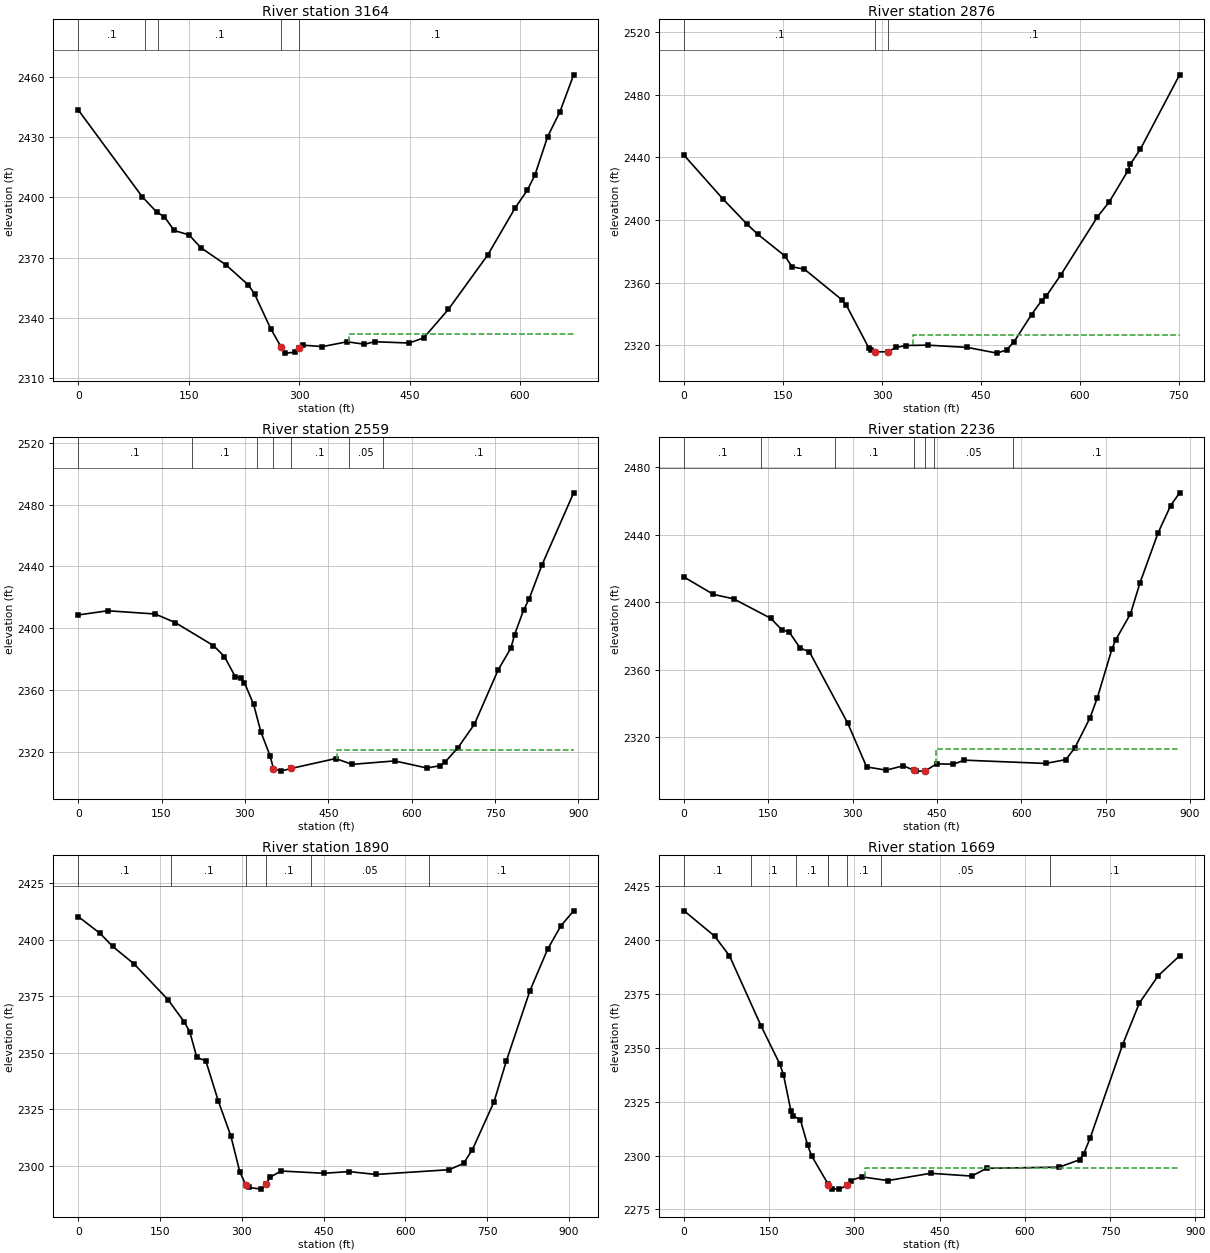
Type RM Length L Ch R = 1 ,3164    ,279.9,288.4,295.3
XS GIS Cut Line= 2
2140739.60229005396328.7543209792140081.61607322396469.379367813
#Sta/Elev= 30
       0 2443.63    86.8 2400.44   106.9 2392.62   116.9 2390.47   130.4 2383.57
   150.5 2381.37   166.8 2374.96   200.8 2366.42   231.2  2356.4   239.5 2351.96
   261.6 2334.56  275.912325.372   281.3 2322.53   294.8    2323  299.242325.026
   304.8 2326.51   331.7 2325.78   365.2 2328.19   388.7 2326.94   402.5 2328.21
   449.1 2327.55   469.2 2330.11   502.8 2344.35   556.4 2371.53   593.3 2394.78
   610.1 2403.78   620.2 2411.17   637.5 2430.32   654.1 2442.59   672.8 2461.05
#Mann= 5 ,-1 , 0
       0      .1       0   90.98      .1       0  108.82      .1       0
  275.91    .045       0  299.24      .1       0
#XS Ineff= 2 , 0
                          368.02         2332.26
Permanent Ineff=
       F       F
Bank Sta=275.91,299.24
XS Rating Curve= 0 ,0
Exp/Cntr=0.3,0.1

Type RM Length L Ch R = 1 ,2876    ,325,317.1,310.2
XS GIS Cut Line= 2
2140745.80568972396254.3125407252140087.16855556395892.984523222
#Sta/Elev= 30
       0 2441.25    58.9 2413.36    94.9  2397.5   111.3 2390.95   152.5 2377.11
   163.7 2370.08   182.4 2368.52   239.9 2348.77     246  2345.5   279.7 2318.49
   283.4 2316.73  289.692315.725  309.752315.857   320.9 2318.55   336.6 2319.81
   369.5 2320.04   429.4 2318.58   474.3 2314.94   488.8 2316.94   500.5 2322.34
   526.7 2339.58     542 2348.44   549.2 2351.46     571 2364.82   626.6 2401.89
   644.9 2411.76   672.5 2431.16   676.4  2435.5   691.8 2445.25   751.2 2492.66
#Mann= 3 ,-1 , 0
       0      .1       0  289.69    .045       0  309.75      .1       0
#XS Ineff= 2 , 0
                          347.26         2326.63
Permanent Ineff=
       F       F
Bank Sta=289.69,309.75
XS Rating Curve= 0 ,0
Exp/Cntr=0.3,0.1

Type RM Length L Ch R = 1 ,2559    ,325.7,323.2,321.9
XS GIS Cut Line= 3
 2140986.6913628395833.3058368122140551.57838789395826.795351148
2140095.84931247395806.178922564
#Sta/Elev= 30
       0 2408.48    53.1 2411.19   138.4  2409.1   174.5 2403.56   243.4 2388.61
   263.1 2381.51   282.7 2368.38   292.6 2367.74   299.2 2364.46   315.6 2350.57
   328.7 2332.66   345.1 2317.34  351.272308.987   364.8  2307.3  382.812309.003
   463.2 2315.44   492.8 2311.68   569.6 2313.91   627.4 2309.32   650.4 2310.77
   660.7 2313.43   683.3 2322.49   712.8 2337.65   755.5  2372.8   778.5 2387.03
   785.1 2395.68   801.5 2411.76   811.4 2418.97   834.4 2440.88   891.4 2487.59
#Mann= 7 ,-1 , 0
       0      .1       0  205.23      .1       0  322.01      .1       0
  351.27    .045       0  382.81      .1       0  486.43     .05       0
  548.97      .1       0
#XS Ineff= 1 ,-1
  466.33  891.35 2320.85
Permanent Ineff=
       F
Bank Sta=351.27,382.81
XS Rating Curve= 0 ,0
Exp/Cntr=0.3,0.1

Type RM Length L Ch R = 1 ,2236    ,347.5,346.1,342.7
XS GIS Cut Line= 2
2140962.81969139395503.4446198942140081.74336955395525.146020055
#Sta/Elev= 30
       0 2414.83    52.2  2404.6    88.3 2401.93   153.9 2390.44   173.6 2383.65
   186.7 2382.35   206.4 2372.76   222.8 2370.56   291.3 2328.01   324.6 2302.24
   359.4 2300.34   390.2 2302.94  408.542300.219   413.2 2299.75  428.572299.817
   449.1 2304.09   478.8 2303.85   498.5 2306.26   642.9  2304.3     679 2306.58
   695.1 2313.64   721.7 2331.18   734.8 2343.07     761 2372.22   767.6 2377.59
   793.9 2393.03     811  2411.6   843.1 2441.17   865.5 2457.34   881.3 2464.86
#Mann= 7 ,-1 , 0
       0      .1       0  137.62      .1       0  267.71      .1       0
  408.54    .045       0  428.57      .1       0   445.1     .05       0
  585.51      .1       0
#XS Ineff= 2 , 0
                          448.78         2312.91
Permanent Ineff=
       F       F
Bank Sta=408.54,428.57
XS Rating Curve= 0 ,0
Exp/Cntr=0.3,0.1

Type RM Length L Ch R = 1 ,1890    ,222,221,219.9
XS GIS Cut Line= 3
2140957.39450538  395222.41171742140572.19481647395203.965560064
2140049.19126931 395194.19983156
#Sta/Elev= 30
       0 2410.19    40.2 2402.73    63.2 2396.97   102.6 2389.21     165 2373.32
   194.6 2363.54   204.6 2359.23   217.6 2347.84     234 2346.39     257 2328.57
     280 2313.07   296.4 2297.24  307.212291.586   312.8 2290.34   335.8 2289.59
   344.82291.861   352.2 2294.88     372 2297.61   450.6  2296.6   496.7 2297.35
   545.9 2296.08   680.4 2298.18   706.7 2300.96   723.1 2307.09   762.5 2328.12
   785.4 2346.39   828.5 2377.35   860.9  2395.7   885.3 2406.07   908.7 2412.72
#Mann= 6 ,-1 , 0
       0      .1       0   171.1      .1       0  307.21    .045       0
   344.8      .1       0  427.27     .05       0  643.75      .1       0
Bank Sta=307.21,344.8
XS Rating Curve= 0 ,0
Exp/Cntr=0.3,0.1

Type RM Length L Ch R = 1 ,1669    ,117.3,113.2,109.3
XS GIS Cut Line= 2
2140918.33191948394980.4410727322140045.93602647395001.057501316
#Sta/Elev= 30
       0 2413.62    53.6 2401.89    79.9 2392.72   135.7 2360.07   168.5 2342.46
     175 2337.48   188.2 2320.59   191.4 2318.44   204.6 2316.71   217.7 2304.67
   224.6 2299.83   253.8 2286.64   254.1 2286.51   260.4 2284.51   273.5 2284.41
   286.6 2286.16   293.2 2288.41   312.9 2290.12   358.8 2288.38   434.3 2291.77
   506.5 2290.46   532.7 2294.07   660.7 2294.62   696.8 2298.09   703.4 2300.64
   715.2  2308.2   772.3 2351.54   801.8 2370.82   834.7 2383.42   872.6 2392.74
#Mann= 8 ,-1 , 0
       0      .1       0  117.09      .1       0  196.31      .1       0
   253.8    .045       0   254.1    .045       0   286.6      .1       0
   346.7     .05       0  644.83      .1       0
#XS Ineff= 2 , 0
                          318.57         2294.36
Permanent Ineff=
       F       F
Bank Sta=254.1,286.6
XS Rating Curve= 0 ,0
Exp/Cntr=0.5,0.3

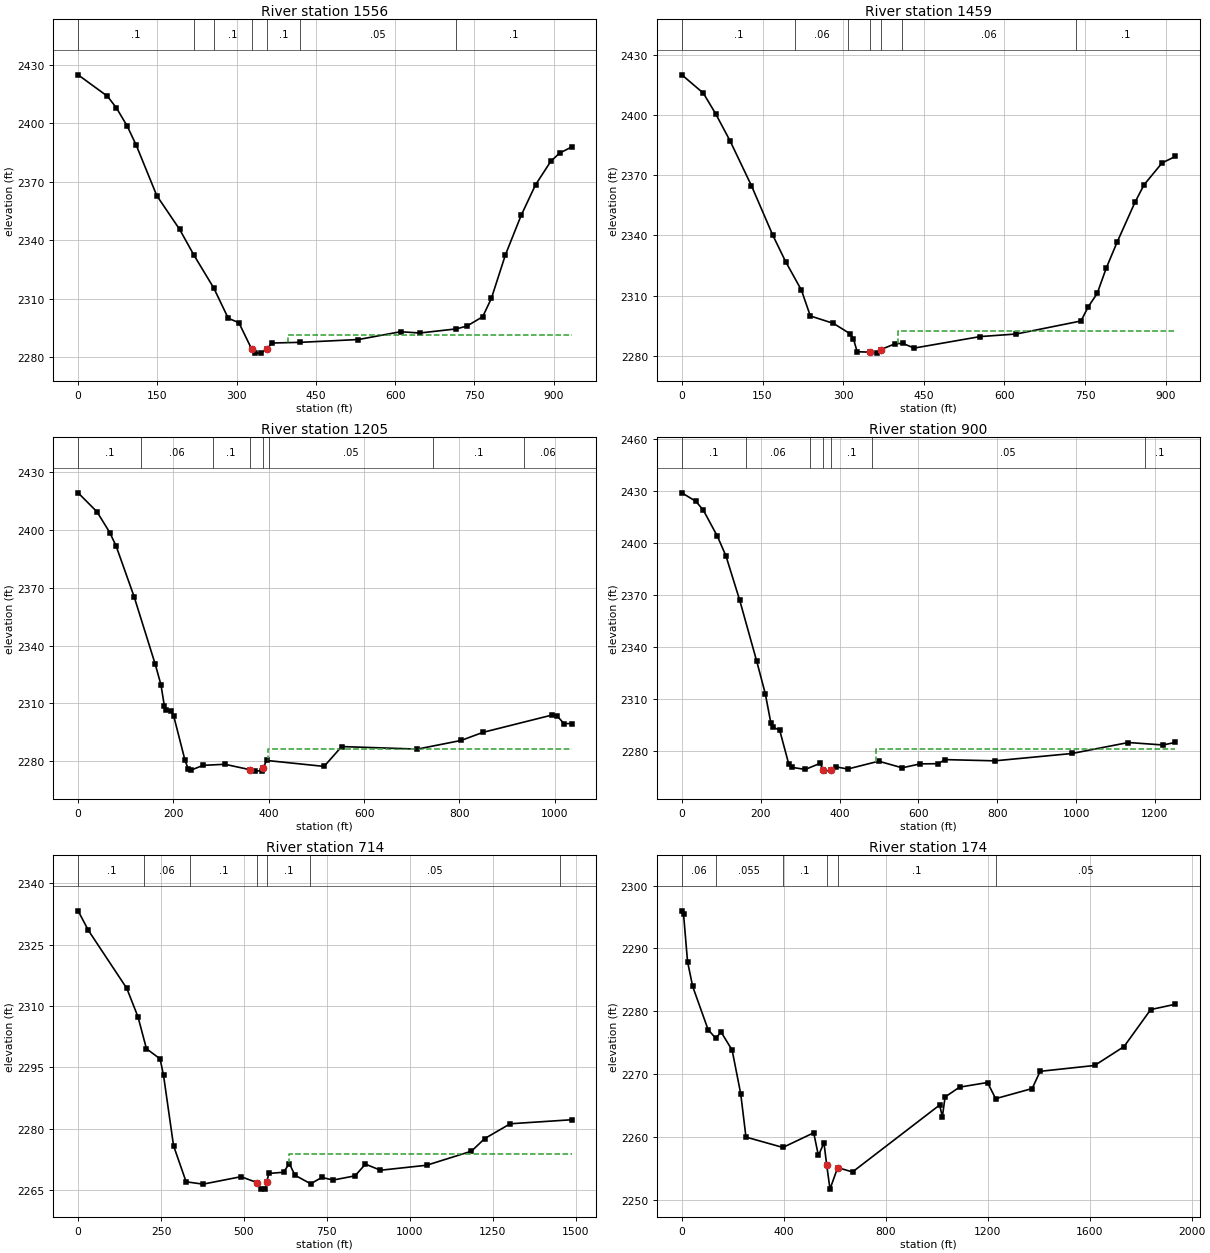
Type RM Length L Ch R = 1 ,1556    ,96.6,96.1,95.4
XS GIS Cut Line= 4
2140957.39450538394780.7882568092140585.21545972394888.210286066
2140481.04900138394913.1669290662140044.85105489394967.420429483
#Sta/Elev= 30
       0    2425    55.5 2414.01    72.5 2408.04      93 2398.65   110.1 2388.82
   148.9 2362.96   192.1 2345.64   219.4 2332.31   256.9 2315.43   284.2 2299.94
   304.3 2297.69  328.782283.968   335.5 2282.07   345.7 2282.04  358.072284.169
   366.2 2287.23   420.4 2287.58   530.6 2289.03   610.4 2293.03   646.7 2292.38
   715.9 2294.49     736 2295.94   765.8 2300.75   782.3 2310.21   808.7 2332.46
   838.5 2352.75   865.8  2368.5   894.7 2380.58   911.2 2384.74     934 2387.93
#Mann= 7 ,-1 , 0
       0      .1       0   219.4     .06       0   256.9      .1       0
  328.78    .045       0  358.07      .1       0   420.4     .05       0
   715.9      .1       0
#XS Ineff= 2 , 0
          288.78  2291.4     398          2291.4
Permanent Ineff=
       F       F
Bank Sta=328.78,358.07
XS Rating Curve= 0 ,0
Exp/Cntr=0.5,0.3

Type RM Length L Ch R = 1 ,1459    ,249.5,254.4,260.1
XS GIS Cut Line= 5
2140943.72261672394729.2411158082140655.96203738394770.907699138
2140557.00390197394798.2514764822140447.62879264394833.407574147
2140046.58694381394915.438906148
#Sta/Elev= 30
       0 2420.19      40 2411.03    63.2  2400.6    89.8 2387.15   129.5  2364.8
   169.3 2340.03   192.9    2327   222.4  2312.7   238.9 2299.83     282  2296.1
   312.4 2291.03   319.2 2288.33     326 2281.97  350.072281.744   363.5 2281.27
  370.222283.076   397.3 2286.02   411.4 2286.08     432 2283.78   554.7 2289.53
   621.7 2290.81   742.3 2297.32   755.7 2304.39   772.4 2311.05   789.2 2323.67
   809.2 2336.52   842.7 2356.57   859.5 2365.29   893.1 2376.22   917.7 2379.43
#Mann= 7 ,-1 , 0
       0      .1       0  210.11     .06       0  309.56    .055       0
  350.07    .045       0  370.22    .055       0  409.56     .06       0
  733.53      .1       0
#XS Ineff= 1 ,-1
  402.38  917.66 2292.46
Permanent Ineff=
       F
Bank Sta=350.07,370.22
XS Rating Curve= 0 ,0
Exp/Cntr=0.5,0.3

Type RM Length L Ch R = 1 ,1205    ,298.9,304.9,313.9
XS GIS Cut Line= 3
2140978.87871438394614.6576835662140433.30598664  394497.4702539
2139990.59755448394675.855723888
#Sta/Elev= 30
       0 2419.38    39.6 2409.54    66.4 2398.77    79.8 2391.72   117.6 2365.39
   161.8 2330.36   173.8 2319.73   181.1 2308.49   183.9 2306.46   194.9 2305.81
   200.4 2303.64   224.1 2280.63   230.8 2276.06   236.4 2275.27     262  2277.8
     308 2278.37  359.922275.586   371.4 2274.81   385.2 2275.08  388.332276.364
   395.3 2280.36   516.1 2277.26     553 2287.57   711.9 2286.25   803.8 2290.76
   849.1 2294.93   994.9 2303.98  1005.5 2303.33  1019.6 2299.44  1035.3 2299.54
#Mann= 8 ,-1 , 0
       0      .1       0  131.85     .06       0   282.5      .1       0
  359.92    .045       0  388.33      .1       0  399.54     .05       0
  743.92      .1       0   936.5     .06       0
#XS Ineff= 2 , 0
                          398.64         2286.13
Permanent Ineff=
       F       F
Bank Sta=359.92,388.33
XS Rating Curve= 0 ,0
Exp/Cntr=0.3,0.1

Type RM Length L Ch R = 1 ,900     ,186.6,185.8,182.1
XS GIS Cut Line= 4
2141059.60788363394561.2722916452140726.27456081 394243.56393756
 2140502.3163473394261.7932318152139993.20155188394510.491225228
#Sta/Elev= 30
       0 2428.97    35.7 2424.05    54.7 2418.88    90.3 2403.84   111.8 2392.61
   146.8 2366.99   190.1 2331.66   211.6 2313.15   225.9 2296.09   230.6 2293.74
   248.1  2292.1   271.3 2272.39   278.2 2270.63     313 2269.39   350.8  2272.9
   358.82268.945   359.9 2268.41   378.82268.811   392.3 2270.83   420.8 2269.62
   499.3 2274.14   558.9 2270.32   604.7  2272.6   650.7 2272.69   667.2 2275.06
   793.9 2274.35     990 2278.59  1132.6 2284.92  1220.2  2283.5  1251.8 2284.95
#Mann= 7 ,-1 , 0
       0      .1       0   163.9     .06       0  324.74      .1       0
   358.8    .045       0   378.8      .1       0  481.26     .05       0
 1174.21      .1       0
#XS Ineff= 2 , 0
                           493.6         2281.03
Permanent Ineff=
       F       F
Bank Sta=358.8,378.8
XS Rating Curve= 0 ,0
Exp/Cntr=0.3,0.1

Type RM Length L Ch R = 1 ,714     ,530.1,539.9,539.6
XS GIS Cut Line= 4
2141256.66818506394458.0024850672140904.23745947394166.336073637
 2140690.6958918394084.7387958912139991.04309164394475.363670811
#Sta/Elev= 30
       0  2333.3      31 2328.52   146.8 2314.33   180.6 2307.35     206 2299.57
   247.1 2297.09   257.5 2293.08   287.7 2275.85   325.6 2267.01   376.7 2266.44
   491.1 2268.26  539.112266.823   551.9 2265.22     563 2265.26   568.52266.927
   574.8 2269.05   619.2 2269.35   636.7 2271.47   653.6 2268.63   700.9 2266.53
   734.7 2268.08   768.6 2267.44   834.8 2268.47   866.1 2271.34   911.3 2269.84
  1050.4 2271.06  1185.6  2274.5  1225.5 2277.58  1302.6 2281.21  1487.4 2282.19
#Mann= 7 ,-1 , 0
       0      .1       0  200.04     .06       0  336.28      .1       0
  539.11    .045       0   568.5      .1       0  698.54     .05       0
 1452.45      .1       0
#XS Ineff= 1 ,-1
  635.65 1487.38 2273.77
Permanent Ineff=
       F
Bank Sta=539.11,568.5
XS Rating Curve= 0 ,0
Exp/Cntr=0.3,0.1

Type RM Length L Ch R = 1 ,174     ,144.1,139.5,110.4
XS GIS Cut Line= 6
2141429.47013106394463.2194806312141310.72119183393947.893895287
2141243.50481114393871.7153304972141001.10317058393938.240955337
2140661.74853513394076.3642455562140065.76329295394419.167787111
#Sta/Elev= 30
       0 2295.98     6.5 2295.54    22.3 2287.91    42.5 2283.95   103.1 2277.07
   133.4 2275.69   153.6 2276.73   197.3 2273.81     231 2266.86   251.5 2259.99
   396.4 2258.34   517.2 2260.67   535.6 2257.06   557.5 2259.07   568.2 2255.55
   581.1 2251.71   611.3 2255.14   669.4 2254.44  1011.3 2265.09  1021.9 2263.22
  1032.6 2266.37  1089.2 2267.93    1199 2268.67  1230.9  2266.1  1374.1 2267.71
  1405.4 2270.45  1619.2 2271.38  1734.6 2274.39  1839.1 2280.27  1935.7 2281.12
#Mann= 6 ,-1 , 0
       0     .06       0   133.4    .055       0   396.4      .1       0
   568.2    .045       0   611.3      .1       0  1230.9     .05       0
Bank Sta=568.2,611.3
XS Rating Curve= 0 ,0
Exp/Cntr(USF)=0,0
Exp/Cntr=0.3,0.1

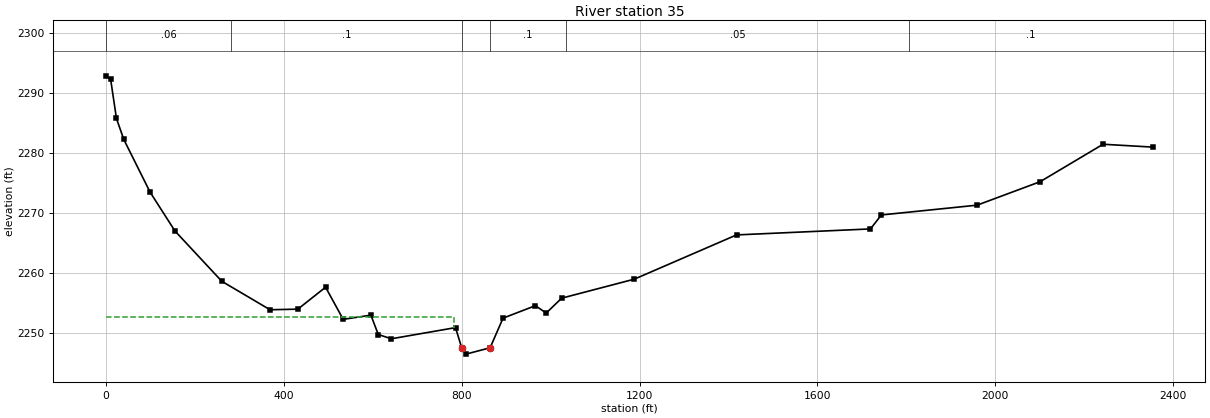
Type RM Length L Ch R = 1 ,35      ,355.49,346,294.82
XS GIS Cut Line= 6
2141573.41688682394527.841649905 2141529.7298683393869.059809039
2141336.36831356393808.9806903482141083.39883803393896.086916205
2140678.54302897394055.2247473152139992.77930863394445.849950314
#Sta/Elev= 30
       0 2292.85    10.9 2292.28      24 2285.74    40.5 2282.24    99.7 2273.44
   155.6 2266.97   260.8 2258.59   369.3 2253.84   431.8 2253.94   494.2  2257.6
   533.7 2252.24   596.1 2252.94   612.6 2249.71     642    2249   786.3 2250.86
     800 2247.54   809.7 2246.44   864.1  2247.5   893.1 2252.44   965.9 2254.52
   990.2 2253.29  1024.9 2255.77  1188.2 2258.94  1418.1 2266.32  1719.2 2267.32
  1743.7 2269.65  1958.9 2271.28  2100.5 2275.19  2242.1 2281.44  2354.5 2280.96
#Mann= 6 ,-1 , 0
       0     .06       0  282.62      .1       0     800    .045       0
   864.1      .1       0 1035.44     .05       0 1806.55      .1       0
#XS Ineff= 2 , 0
          782.52 2252.61
Permanent Ineff=
       F       F
Bank Sta=800,864.1
XS Rating Curve= 0 ,0
Exp/Cntr=0.3,0.1
LCMann Table=0

Chan Stop Cuts=-1
Use User Specified Reach Order=0
Composite Channel Slope=5